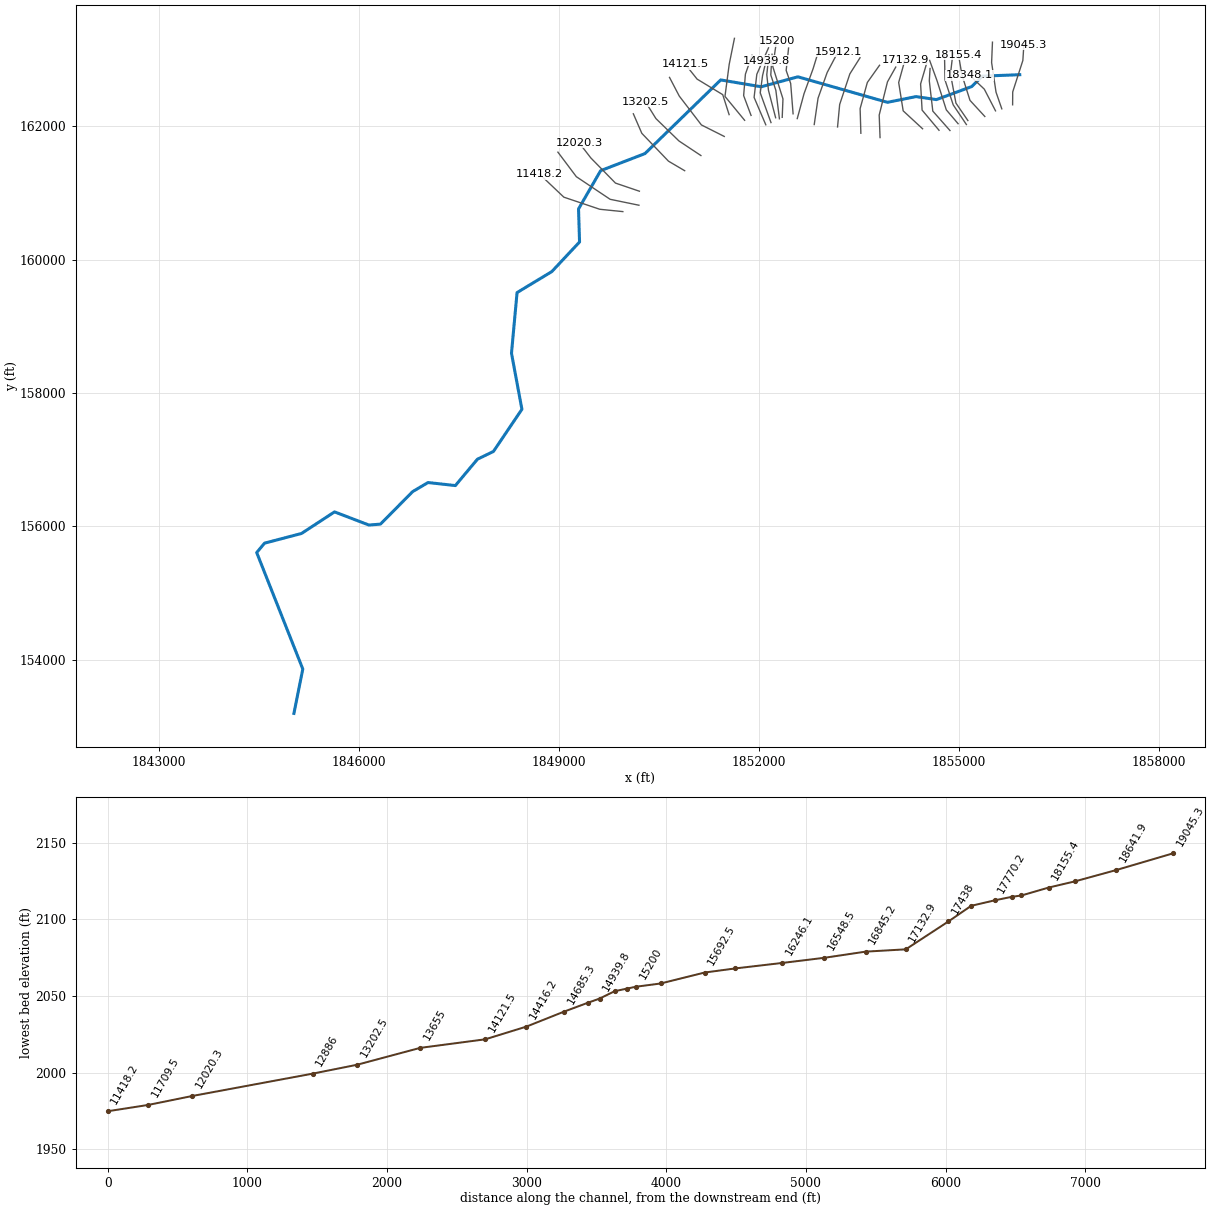
--- Buzzard Branch.prj (project) ---

Proj Title=Buzzard Branch
Current Plan=p01
Default Exp/Contr=0,0
English Units
Geom File=g01
Flow File=f01
Plan File=p01
BEGIN DESCRIPTION:
END DESCRIPTION:
DSS Export Rating Curves= 0
DSS Export Rating Curve Sorted= 0
DSS Export Volume Flow Curves= 0
DXF OffsetX= 0
DXF OffsetY= 0
DXF ScaleX= 0
DXF ScaleY= 0

--- Buzzard Branch.p01 (plan) ---

Plan Title=Floodplain
Program Version=4.00
Geom File=g01
Flow File=f01
K Sum by GR=0
Std Step Tol=0.01
Critical Tol=0.01
Num of Std Step Trials=20
Max Error Tol=0.3
Flow Tol Ratio=0.001
Split Flow NTrial=30
Split Flow Tol=0.02
Split Flow Ratio=0.02
Log Output Level=0
Friction Slope Method=1
Unsteady Friction Slope Method=2
Unsteady Bridges Friction Slope Method=1
Global Log Level=0
CheckData=False
Run HTab=0
Run UNet=0
Run PostProcess=0
UNET Theta=0
UNET Theta Warmup=0
UNET ZTol=0
UNET ZSATol=0
UNET MxIter=0
UNET MaxInSteps=0
UNET DtIC=0
UNET DtMin=0
UNET MaxCRTS=0
UNET WFStab=0
UNET SFStab=0
UNET WFX=0
UNET SFX=0
UNET DSS MLevel=0
UNET DZMax Abort=0
UNET Convert EG Bridges=0
UNET Use Existing IB Tables=0
UNET Froude Limit=0
UNET Froude Power=0
Write IC File=0
Echo Input=False
Echo Output=False
Write Detailed=0

--- Buzzard Branch.f01 (steady flow) ---

Flow Title=NFF Regression Equation
Program Version=4.00
Number of Profiles=1
Profile Names=P100yr
River Rch & RM=Buzzard Branch,Main      ,19045.3
601.1765
River Rch & RM=Buzzard Branch,Main      ,17132.9
652.4519
River Rch & RM=Buzzard Branch,Main      ,16845.2
832.9369
River Rch & RM=Buzzard Branch,Main      ,14416.2
922.0791
River Rch & RM=Buzzard Branch,Main      ,14121.5
1210.794
River Rch & RM=Buzzard Branch,Main      ,12020.3
1245.242
River Rch & RM=Buzzard Branch,Main      ,11709.5
1416.938
River Rch & RM=Buzzard Branch,Main      ,10816.5
1489.443
River Rch & RM=Buzzard Branch,Main      ,9926.8
1591.720
River Rch & RM=Buzzard Branch,Main      ,290.2
1760.950
Boundary for River Rch & Prof#=Buzzard Branch,Main      ,1
Up Type=0
Dn Type=3
Dn Slope=0.039869

--- Buzzard Branch.g01 (geometry) ---

Geom Title=USGS 10m DEM
Program Version=4.00

River Reach=Buzzard Branch  ,Main
Reach XY= 30
     1855916.741      162774.274     1855354.612      162752.488
     1855196.248      162596.323     1854665.372      162400.662
     1854360.511        162445.8     1853931.531      162359.875
     1852586.533       162742.59     1852037.672      162593.244
      1851428.38      162695.694     1850291.347      161591.148
     1849625.996      161334.905     1849294.257      160761.077
     1849309.607      160265.289     1848893.086      159820.999
       1848371.4      159506.096     1848288.095      158596.247
      1848444.47      157756.009     1848016.913      157123.355
     1847776.453      157006.966     1847445.474      156611.722
     1847034.985      156657.206     1846804.569      156521.319
     1846321.285      156033.309     1846148.178       156019.72
     1845631.809      156217.052     1845136.118      155893.287
     1844581.347      155747.947      1844463.52      155607.213
     1845155.615      153859.715     1845022.417      153195.056

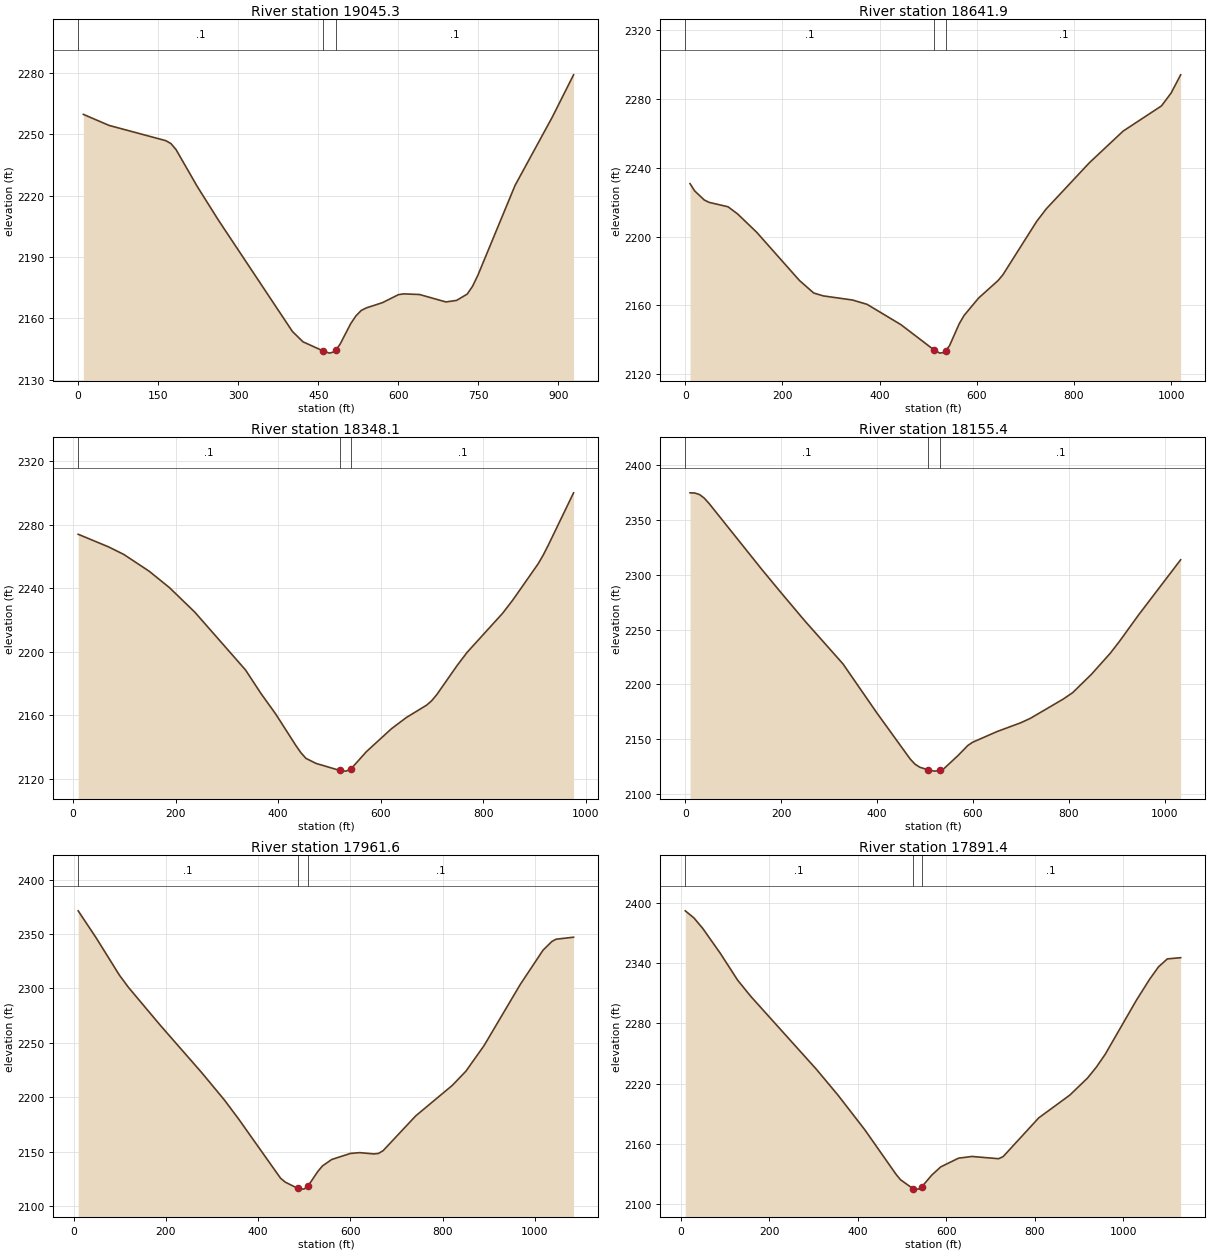
Type RM Length L Ch R = 1 ,19045.3 ,390.4,403.4,416.3
XS GIS Cut Line= 4
     1855809.955      162322.779     1855811.356      162515.899
      1855963.71      162988.197     1855978.945      163226.885
#Sta/Elev= 30
     9.7 2259.75    57.9 2254.36   164.2 2246.91   173.8  2245.5   183.5 2242.52
   222.9 2224.65   262.6 2208.17   401.6 2153.65   421.4  2148.6   458.5 2144.22
     471 2143.07     481  2143.8   483.5 2144.72   490.9 2147.43   510.7 2157.41
   520.7 2161.28   530.6 2163.93   540.5 2165.21   570.3 2167.73   600.1 2171.62
     610 2172.03   639.8 2171.72   689.4 2168.08   709.3 2168.84   729.3 2171.94
   739.2 2175.73   749.2 2181.11   818.9 2225.03   888.7 2258.41   928.6 2279.08
#Mann= 3 , 0 , 0
       0      .1       0   458.5    .045       0   483.5      .1       0
Bank Sta=458.5,483.5
XS Rating Curve= 0 ,0
Exp/Cntr=0.3,0.1

Type RM Length L Ch R = 1 ,18641.9 ,275.7,293.8,311.8
XS GIS Cut Line= 4
     1855647.518      162262.287     1855560.938      162512.113
     1855494.645      162956.582     1855507.384      163262.327
#Sta/Elev= 30
     9.8 2230.74    19.6 2226.48    39.2 2221.25      49 2219.89    88.1 2217.31
   107.7 2213.17   146.9 2202.55     235 2174.51   264.4  2167.2   284.4 2165.51
   344.3 2163.13   374.3 2160.62   444.2 2148.76   511.5 2134.26     524 2132.26
     534 2132.76   536.5 2133.72     544 2136.58     564 2149.33     574 2154.16
   603.9 2164.28   643.9 2174.43   653.9  2177.8   723.7 2208.94   743.4 2216.18
   832.2 2242.98   901.3 2261.27   980.3 2275.93  1000.1 2283.38  1019.8    2294
#Mann= 3 , 0 , 0
       0      .1       0   511.5    .045       0   536.5      .1       0
Bank Sta=511.5,536.5
XS Rating Curve= 0 ,0
Exp/Cntr=0.3,0.1

Type RM Length L Ch R = 1 ,18348.1 ,207.6,192.7,177.8
XS GIS Cut Line= 3
     1855553.288      162232.074     1855385.173      162557.096
     1855164.756      162766.306
#Sta/Elev= 30
     9.9 2274.06    69.2 2266.11    98.9 2261.36   148.3 2250.81   187.9 2240.48
   237.4 2225.02   336.3 2188.63   365.9 2174.06   395.3 2160.82   434.5 2141.08
   444.4  2136.5   454.2 2132.95   473.8 2129.79   520.1 2125.36   532.6 2124.92
   542.4 2126.45   571.8 2137.09   620.8 2151.57   650.2 2158.72   689.6 2166.47
   699.5 2169.27   709.3 2173.05   748.9 2191.36   768.6 2199.73   837.8 2224.32
   857.6 2232.62     907 2255.41   916.9 2260.89   926.8 2267.14   976.2 2300.15
#Mann= 3 , 0 , 0
     9.9      .1       0   520.1    .045       0   542.4      .1       0
Bank Sta=520.1,542.4
XS Rating Curve= 0 ,0
Exp/Cntr=0.3,0.1

Type RM Length L Ch R = 1 ,18155.4 ,197.1,193.8,190.5
XS GIS Cut Line= 4
      1855392.73      162147.632     1855169.791       162389.68
     1855048.767      162771.861      1854997.81      163071.237
#Sta/Elev= 30
      10 2374.88    19.9 2374.71    29.9 2373.27    39.9 2369.94    49.9 2365.06
   159.6 2305.01   199.4 2283.97   249.3 2258.04   329.1 2218.69   399.2 2174.28
   469.4 2131.78   479.4 2127.12   489.4 2124.31     507 2121.97   519.5 2120.77
     532 2121.36   539.5 2122.95   569.6 2135.22   589.6 2144.19   599.7 2147.16
   649.8 2156.77   699.9 2164.92   719.9 2168.92   788.7 2186.59   808.3 2192.42
   847.5  2209.2   886.7 2228.37   906.3 2239.45   945.5 2263.19  1033.6 2313.78
#Mann= 3 , 0 , 0
       0      .1       0     507    .045       0     532      .1       0
Bank Sta=507,532
XS Rating Curve= 0 ,0
Exp/Cntr=0.3,0.1

Type RM Length L Ch R = 1 ,17961.6 ,66.5,70.2,73.9
XS GIS Cut Line= 5
     1855138.605      162086.374     1854959.282      162347.887
     1854877.093      162784.985      1854906.98      163039.025
     1854925.659      163102.535
#Sta/Elev= 30
     9.9 2371.26    49.5 2346.03    99.1 2312.28   118.9 2300.95   188.3 2265.94
   277.5 2222.74   327.2 2197.34   357.5 2180.17   448.5 2125.72   458.6  2122.1
   486.5 2116.22     499 2115.63  507.58 2118.13   529.4 2131.87   539.5 2136.96
   559.7 2142.89   600.1 2148.43   620.3 2149.14   650.7 2147.97   660.8 2148.41
   670.9 2150.94   741.6 2182.91   820.9 2210.91   850.4 2223.97   889.7 2247.44
   968.4 2303.75  1017.6 2335.11  1036.6 2343.07    1046  2345.2  1083.8 2347.03
#Mann= 3 , 0 , 0
     9.9      .1       0   486.5    .045       0  507.58      .1       0
Bank Sta=486.5,507.58
XS Rating Curve= 0 ,0
Exp/Cntr=0.3,0.1

Type RM Length L Ch R = 1 ,17891.4 ,121.5,121.2,120.9
XS GIS Cut Line= 4
     1855116.189        162026.6     1854918.187      162321.735
     1854794.903      162695.324     1854787.431      163076.384
#Sta/Elev= 30
     9.9 2392.14    29.6 2385.05    49.4 2374.63    88.9 2349.95   128.3 2323.06
     158  2306.9     306 2234.38   355.4 2208.32   415.9 2173.86   486.5 2129.49
   496.6 2124.09   524.5  2115.3     537 2114.73  544.54 2116.95   567.2 2128.71
   587.4 2136.89   627.8  2145.6     658 2147.29   718.5 2145.05   728.6 2147.15
     809 2185.73   879.2 2208.42   919.3 2225.42   939.4 2236.37   959.4 2249.18
  1029.6 2302.83  1059.7 2323.88  1079.8 2336.27  1099.8 2344.22  1129.9 2345.43
#Mann= 3 , 0 , 0
     9.9      .1       0   524.5    .045       0  544.54      .1       0
Bank Sta=524.5,544.54
XS Rating Curve= 0 ,0
Exp/Cntr=0.3,0.1

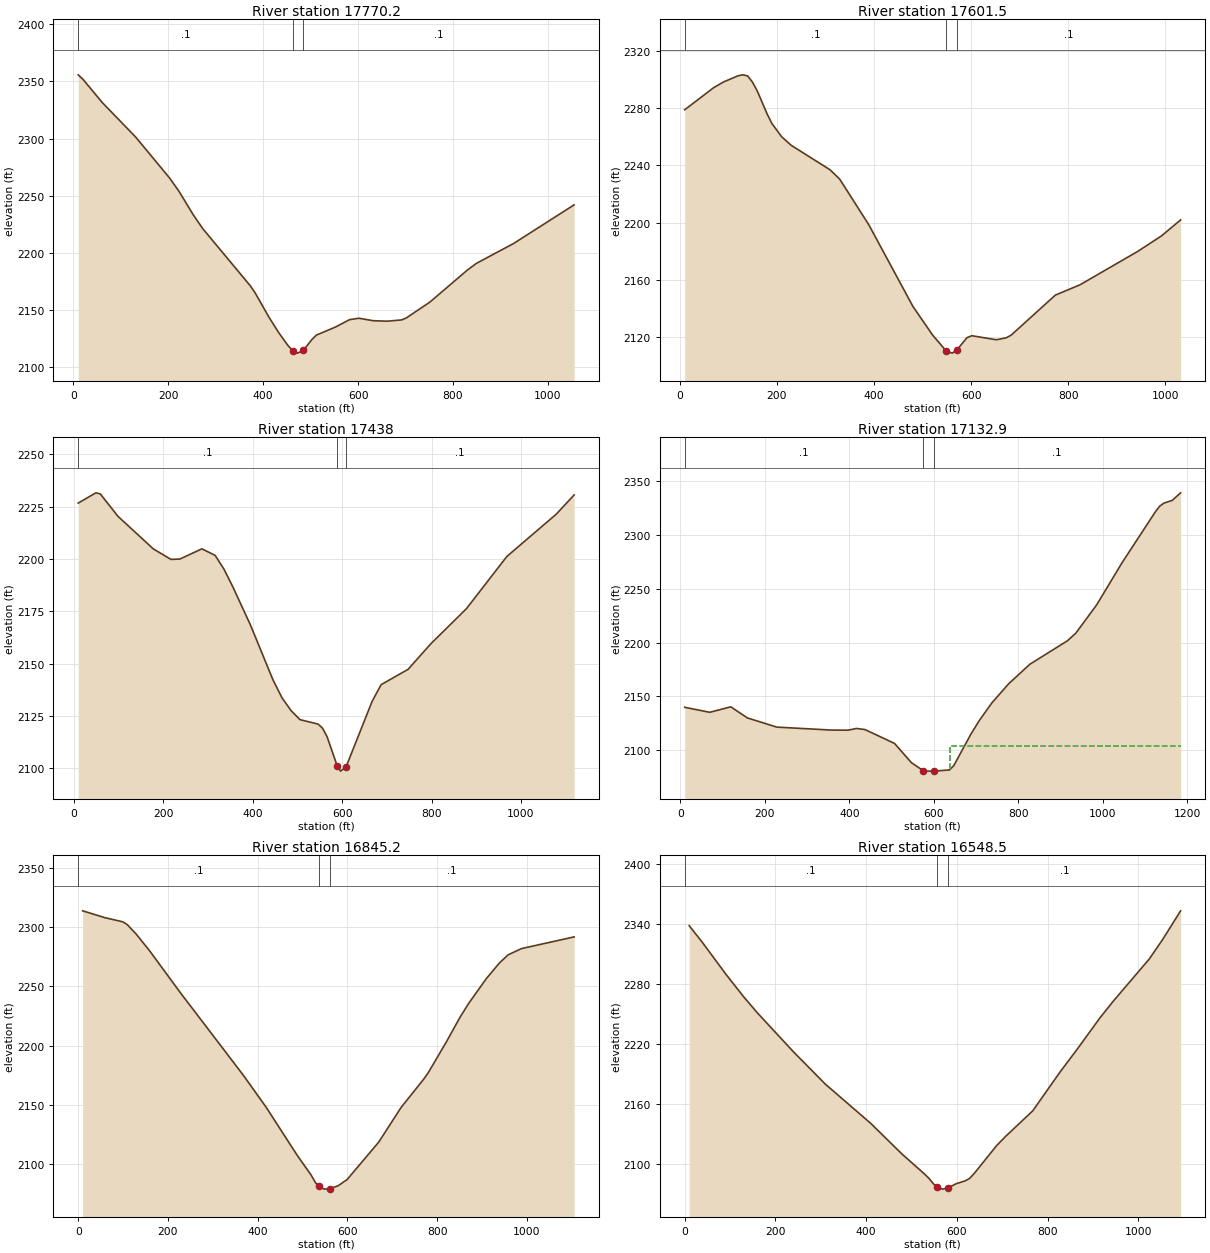
Type RM Length L Ch R = 1 ,17770.2 ,174.1,168.8,163.7
XS GIS Cut Line= 4
      1854991.44      162039.347     1854814.422      162247.029
     1854675.355      162684.116     1854564.671      162988.431
#Sta/Elev= 30
    10.1 2355.71    20.2 2351.77    60.6 2331.58   131.4 2301.23   202.1 2265.83
   222.4 2253.98   252.7  2233.3   272.9 2221.12   372.6 2171.43   382.6 2165.43
   412.5 2143.65   432.4 2130.58   452.4 2119.01   462.3 2114.51   472.3 2112.47
   484.8 2114.93   502.2 2124.15   512.2 2128.27   552.1 2135.22     582 2141.72
   601.9 2142.97   631.9 2140.79   661.8  2140.4   691.7 2141.49   701.6 2143.21
   751.2 2157.04   829.7 2184.84   849.3  2190.9   927.8 2208.29  1055.4 2242.09
#Mann= 3 , 0 , 0
    10.1      .1       0   462.3    .045       0   484.8      .1       0
Bank Sta=462.3,484.8
XS Rating Curve= 0 ,0
Exp/Cntr=0.3,0.1

Type RM Length L Ch R = 1 ,17601.5 ,164.9,163.4,161.8
XS GIS Cut Line= 4
     1854869.621      161936.939     1854611.845      162228.338
     1854559.542       162680.38      1854570.75      162867.175
#Sta/Elev= 30
      10 2278.77    69.8 2294.23    89.8 2298.15   119.7 2302.48   129.7 2303.17
   139.7 2302.42   149.6 2298.08   159.6 2291.83   179.6 2275.99   189.5 2269.26
   209.5 2260.01   229.4 2253.95   309.2 2236.91   329.2 2230.36   389.1 2198.53
   480.1 2141.42   520.5  2121.5   548.5 2110.39     561 2108.88   571.1 2111.36
   591.3 2119.69   601.4 2121.03     652 2118.21   672.2 2119.59   682.3 2121.44
   773.3 2149.39   823.9 2156.56   942.6 2179.83   991.8 2190.72  1031.2 2201.89
#Mann= 3 , 0 , 0
      10      .1       0   548.5    .045       0   571.1      .1       0
Bank Sta=548.5,571.1
XS Rating Curve= 0 ,0
Exp/Cntr=0.3,0.1

Type RM Length L Ch R = 1 ,17438   ,302.4,305.1,307.9
XS GIS Cut Line= 4
     1854705.242      161940.675     1854451.201      162243.282
     1854428.786       162635.55     1854522.183        162953.1
#Sta/Elev= 30
     9.9 2226.72    49.4 2231.62    59.3 2231.11    98.8 2220.39   177.8 2204.85
   217.3 2199.82   237.1 2199.97   286.5 2204.87   316.1 2201.74   335.8  2195.2
   355.6 2186.75   395.1 2168.48   445.5 2142.25   465.6 2133.71   485.8  2127.6
   505.9 2123.25   546.2 2121.15   556.3 2119.19   566.4 2115.14  588.91 2101.27
   596.6 2098.66   609.1 2100.78   667.1 2131.94   687.3 2139.96   747.7  2147.3
     798  2159.4   878.3 2176.32   968.6 2201.23  1078.9  2221.4    1119 2230.62
#Mann= 3 , 0 , 0
     9.9      .1       0  588.91    .045       0   609.1      .1       0
Bank Sta=588.91,609.1
XS Rating Curve= 0 ,0
Exp/Cntr=0.3,0.1

Type RM Length L Ch R = 1 ,17132.9 ,298.8,287.6,276.5
XS GIS Cut Line= 4
     1854458.673       161963.09     1854167.274      162232.074
     1854099.684      162657.207     1854195.229       163001.17
#Sta/Elev= 30
     9.9 2139.88    69.4 2135.22     119 2140.34   158.6 2129.97     228 2121.45
   356.9 2118.69   396.6 2118.57   416.6 2120.19   436.6 2119.19   506.7 2106.26
   546.7 2088.37   574.3 2081.03   586.8 2080.49   599.3  2080.5   636.8 2081.58
   646.8 2085.49   686.9 2114.46   706.9 2127.26   736.9 2143.88     777 2161.78
     827  2179.9   916.3 2201.83   936.1 2208.95   985.7 2235.47  1045.2 2274.31
  1124.5 2321.93  1134.4 2326.97  1144.4 2329.86  1164.2 2332.41    1184 2339.44
#Mann= 3 , 0 , 0
     9.9      .1       0   574.3    .045       0   599.3      .1       0
#XS Ineff= 2 , 0
                           638.6         2103.87
Permanent Ineff=
       F       F
Bank Sta=574.3,599.3
XS Rating Curve= 0 ,0
Exp/Cntr=0.3,0.1

Type RM Length L Ch R = 1 ,16845.2 ,297.4,296.7,296
XS GIS Cut Line= 4
     1853820.062      161831.191     1853807.322      162168.785
     1853931.315      162666.369      1854055.74       162888.56
#Sta/Elev= 30
     9.9  2313.6    59.6 2307.82    99.4 2304.33   109.3 2301.98   129.2    2294
     159 2279.98   228.5 2244.16     368    2175   418.3 2148.34   488.7 2107.15
   518.8 2091.02   528.9 2084.41   536.5 2081.25   538.9 2080.26     549 2078.99
   561.5 2079.46   579.2  2081.8   599.3 2087.07   669.6 2118.54   719.9 2147.97
   770.2  2171.8   780.2 2177.17   820.5 2203.09   850.6 2223.67   870.2 2235.53
   909.4 2256.37   938.8 2269.66   958.4 2276.55   987.8 2281.75  1105.3 2291.63
#Mann= 3 , 0 , 0
       0      .1       0   536.5    .045       0   561.5      .1       0
Bank Sta=536.5,561.5
XS Rating Curve= 0 ,0
Exp/Cntr=0.3,0.1

Type RM Length L Ch R = 1 ,16548.5 ,303.9,302.5,301
XS GIS Cut Line= 4
     1853532.174      161895.844     1853520.966      162265.697
     1853629.307      162657.965     1853812.365      162915.741
#Sta/Elev= 30
      10 2338.35      40 2321.08      90 2290.34     130 2267.29     160 2251.32
     240 2212.13     310 2179.95   409.7 2140.87   479.2 2109.97   528.8    2090
   538.8 2085.53   548.7 2080.09     556 2077.15   558.6  2076.1   568.5 2074.96
     581 2076.27   598.3 2080.36   618.2 2083.21   628.1 2085.74     638 2090.51
   687.6 2118.52   707.5 2127.75   767.1 2153.19   826.4 2191.46   865.9 2215.31
   915.3 2246.19   944.9    2263    1024 2305.05  1053.6  2324.6  1093.1 2353.21
#Mann= 3 , 0 , 0
       0      .1       0     556    .045       0     581      .1       0
Bank Sta=556,581
XS Rating Curve= 0 ,0
Exp/Cntr=0.3,0.1

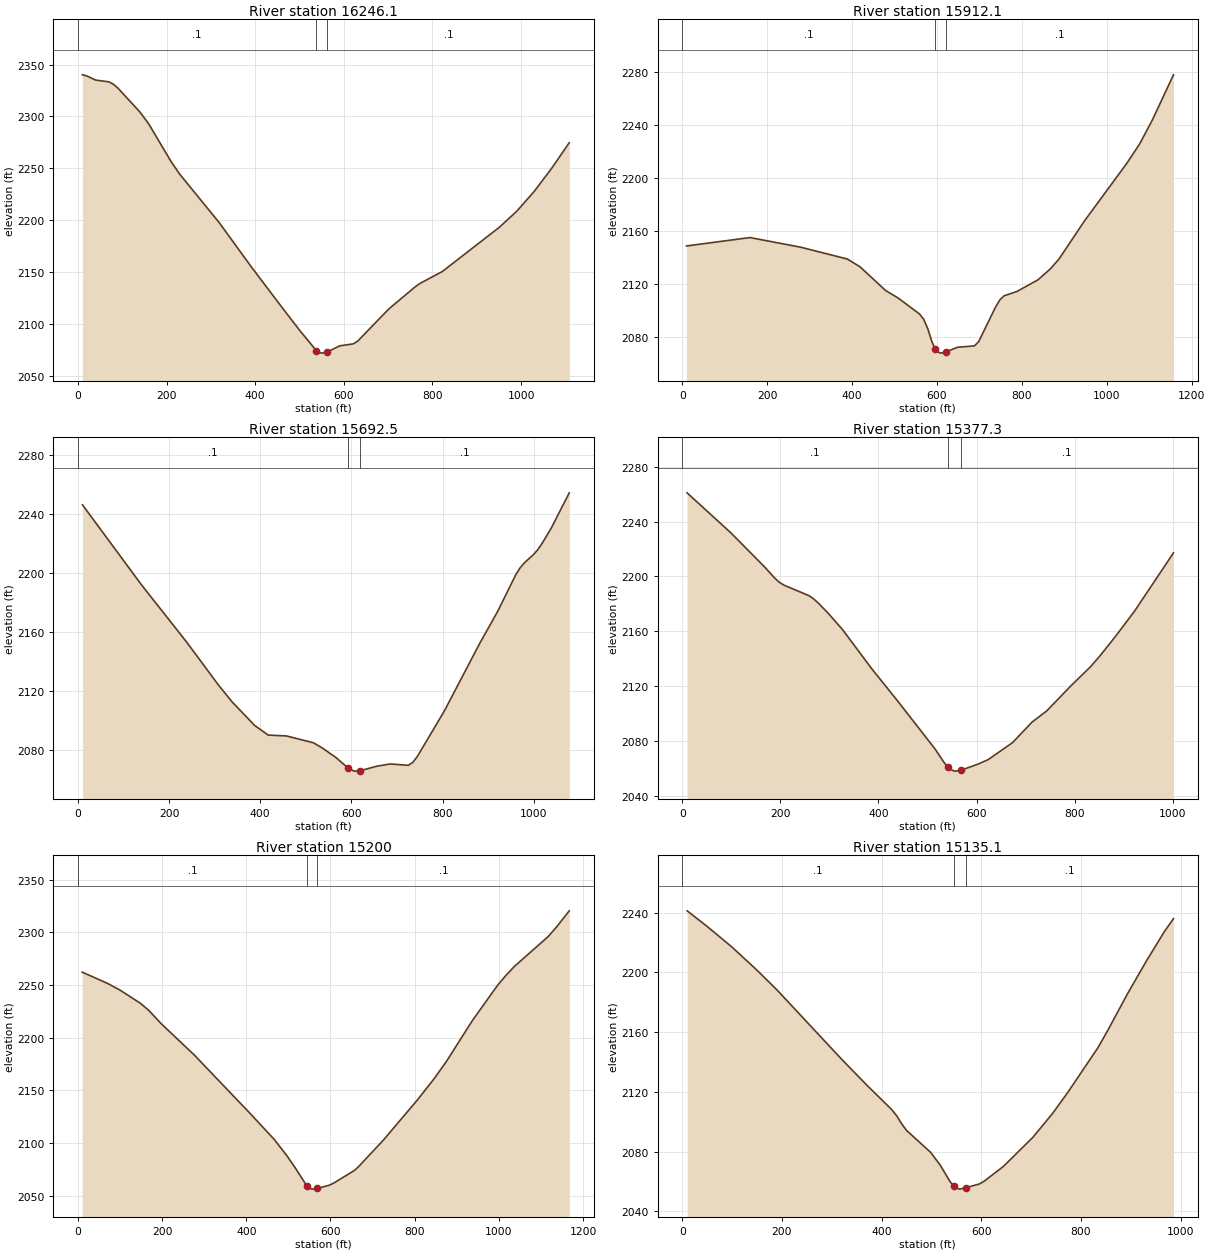
Type RM Length L Ch R = 1 ,16246.1 ,334.5,334,333.5
XS GIS Cut Line= 4
     1853182.143      161990.297     1853213.991       162327.89
     1853366.864      162786.508     1853519.736      163028.556
#Sta/Elev= 30
      10  2340.1    19.9 2339.03    39.9 2335.03    69.8 2333.33    79.8 2331.08
    89.8 2327.44   139.6 2304.32   159.6 2292.83   209.4 2256.94   229.4 2244.39
   319.1 2197.31   389.4 2155.87   459.9 2116.03   500.2 2093.64   538.1 2073.96
   540.5 2072.78   550.6 2071.59   563.1 2072.75   590.9 2078.63   621.1 2080.51
   631.2 2083.13   701.7 2114.28   762.1 2135.92   772.2  2138.9   822.5 2150.39
   950.9 2192.98   990.3 2208.49  1029.8 2227.65  1069.3 2250.06  1108.8  2274.6
#Mann= 3 , 0 , 0
       0      .1       0   538.1    .045       0   563.1      .1       0
Bank Sta=538.1,563.1
XS Rating Curve= 0 ,0
Exp/Cntr=0.3,0.1

Type RM Length L Ch R = 1 ,15912.1 ,219.8,219.6,219.3
XS GIS Cut Line= 4
     1852832.116      162026.608     1852889.443      162421.529
      1853026.28      162806.935     1853188.818      163115.825
#Sta/Elev= 30
      10 2148.78   159.6 2155.12   279.3 2147.83   389.1 2138.93     419 2133.04
   478.9 2115.27   508.8  2109.5   558.7  2097.6   568.6 2093.63   578.6 2086.24
   588.6 2076.23     596 2071.21   598.6 2069.45   608.5 2068.04     621 2068.94
   648.4 2072.46   688.3 2073.49   698.3 2076.71   738.2 2102.87   748.2 2108.18
   758.2 2111.24   788.1 2114.45     838 2123.29   867.9 2131.77   887.8 2139.11
   947.7 2167.76  1047.4 2211.16  1077.3 2225.62  1107.2 2243.62  1157.1 2277.73
#Mann= 3 , 0 , 0
       0      .1       0     596    .045       0     621      .1       0
Bank Sta=596,621
XS Rating Curve= 0 ,0
Exp/Cntr=0.3,0.1

Type RM Length L Ch R = 1 ,15692.5 ,296.4,315.2,334
XS GIS Cut Line= 4
     1852577.328      162115.784     1852679.295      162490.019
     1852814.703       162862.39     1852900.809       163143.63
#Sta/Elev= 30
     9.9 2246.31   139.2 2192.02   238.7 2152.98   308.3 2123.85   338.2 2112.45
   387.9 2096.36   417.6 2089.84   457.2 2089.29   516.7 2084.63   536.5 2081.02
   566.2  2074.6   593.3 2067.32   605.8 2065.36   618.3 2065.57   655.3 2068.65
     685 2070.22   724.7 2069.32   734.6 2071.21   744.5 2075.17   803.7 2106.04
   882.1  2152.4   921.4 2174.08   960.6 2198.71   970.4 2203.53   980.2 2207.06
   999.8 2212.56  1009.6 2216.05  1019.4 2220.52    1039 2230.69  1078.2 2254.48
#Mann= 3 , 0 , 0
       0      .1       0   593.3    .045       0   618.3      .1       0
Bank Sta=593.3,618.3
XS Rating Curve= 0 ,0
Exp/Cntr=0.3,0.1

Type RM Length L Ch R = 1 ,15377.3 ,178,177.3,176.5
XS GIS Cut Line= 4
     1852514.872       162187.77     1852478.602      162642.353
     1852410.898       162838.21     1852447.168      163174.311
#Sta/Elev= 30
     9.9 2260.95    99.1 2231.83   168.5 2206.77   188.4  2198.9   198.3 2195.69
   208.2 2193.56   257.8 2186.14   267.7 2183.74   277.6 2180.55   297.4 2173.28
   327.1 2161.17   386.6 2132.65   436.2 2110.63   515.2 2074.41     535 2063.86
   542.2 2060.91   544.8 2059.84   554.7 2058.21   567.2 2058.72     604 2063.46
   623.8 2066.64   673.2 2078.95     713 2093.93   742.8 2102.03   792.5 2120.45
   832.3 2134.29   852.2 2142.52     882 2155.87   921.8 2174.69  1001.3 2217.22
#Mann= 3 , 0 , 0
       0      .1       0   542.2    .045       0   567.2      .1       0
Bank Sta=542.2,567.2
XS Rating Curve= 0 ,0
Exp/Cntr=0.3,0.1

Type RM Length L Ch R = 1 ,15200   ,64.6,65,65.3
XS GIS Cut Line= 4
     1852351.634      162134.941     1852362.841      162411.397
      1852209.67      162897.062     1852265.708      163274.386
#Sta/Elev= 30
     9.9 2262.11    69.2 2251.63    98.8 2245.33   148.2 2232.59     168 2225.92
   197.6 2213.24   276.7 2183.31   406.5 2129.02   466.4 2103.27   496.4 2087.86
   516.3 2076.25   543.8 2059.14   546.3 2057.72   556.3 2056.09   568.8 2056.73
   596.2 2059.68   606.2 2061.48   656.1 2073.63   666.1 2077.16     726 2102.77
     806 2140.52   846.2 2160.88   876.3  2177.8   936.5 2215.73   996.7 2249.44
  1016.8 2258.95  1036.9  2267.5  1117.2 2295.86  1137.3 2305.02  1167.4 2320.33
#Mann= 3 , 0 , 0
       0      .1       0   543.8    .045       0   568.8      .1       0
Bank Sta=543.8,568.8
XS Rating Curve= 0 ,0
Exp/Cntr=0.3,0.1

Type RM Length L Ch R = 1 ,15135.1 ,93.1,87.2,81
XS GIS Cut Line= 4
      1852309.76      162112.956      1852255.98      162540.034
     1852180.055      162770.973     1852199.036         163081.
#Sta/Elev= 30
      10 2241.16    50.1 2230.71   100.1 2216.82   150.2 2201.38   190.2 2188.21
   320.3 2141.67   370.4 2124.49   420.4 2108.11   430.5 2103.89   440.2 2098.67
   449.9 2094.23   498.5 2079.47     518 2070.81   537.4  2059.9   544.4 2057.06
   547.1 2055.97   556.9 2054.85   569.4 2055.81   595.8 2058.24   605.5 2060.05
   644.4 2070.02   703.7 2089.55   743.8 2105.79     774 2119.75   834.2 2149.52
   854.3 2161.35   894.4 2186.15   931.6 2207.64   967.7 2227.33   985.8 2235.93
#Mann= 3 , 0 , 0
       0      .1       0   544.4    .045       0   569.4      .1       0
Bank Sta=544.4,569.4
XS Rating Curve= 0 ,0
Exp/Cntr=0.3,0.1

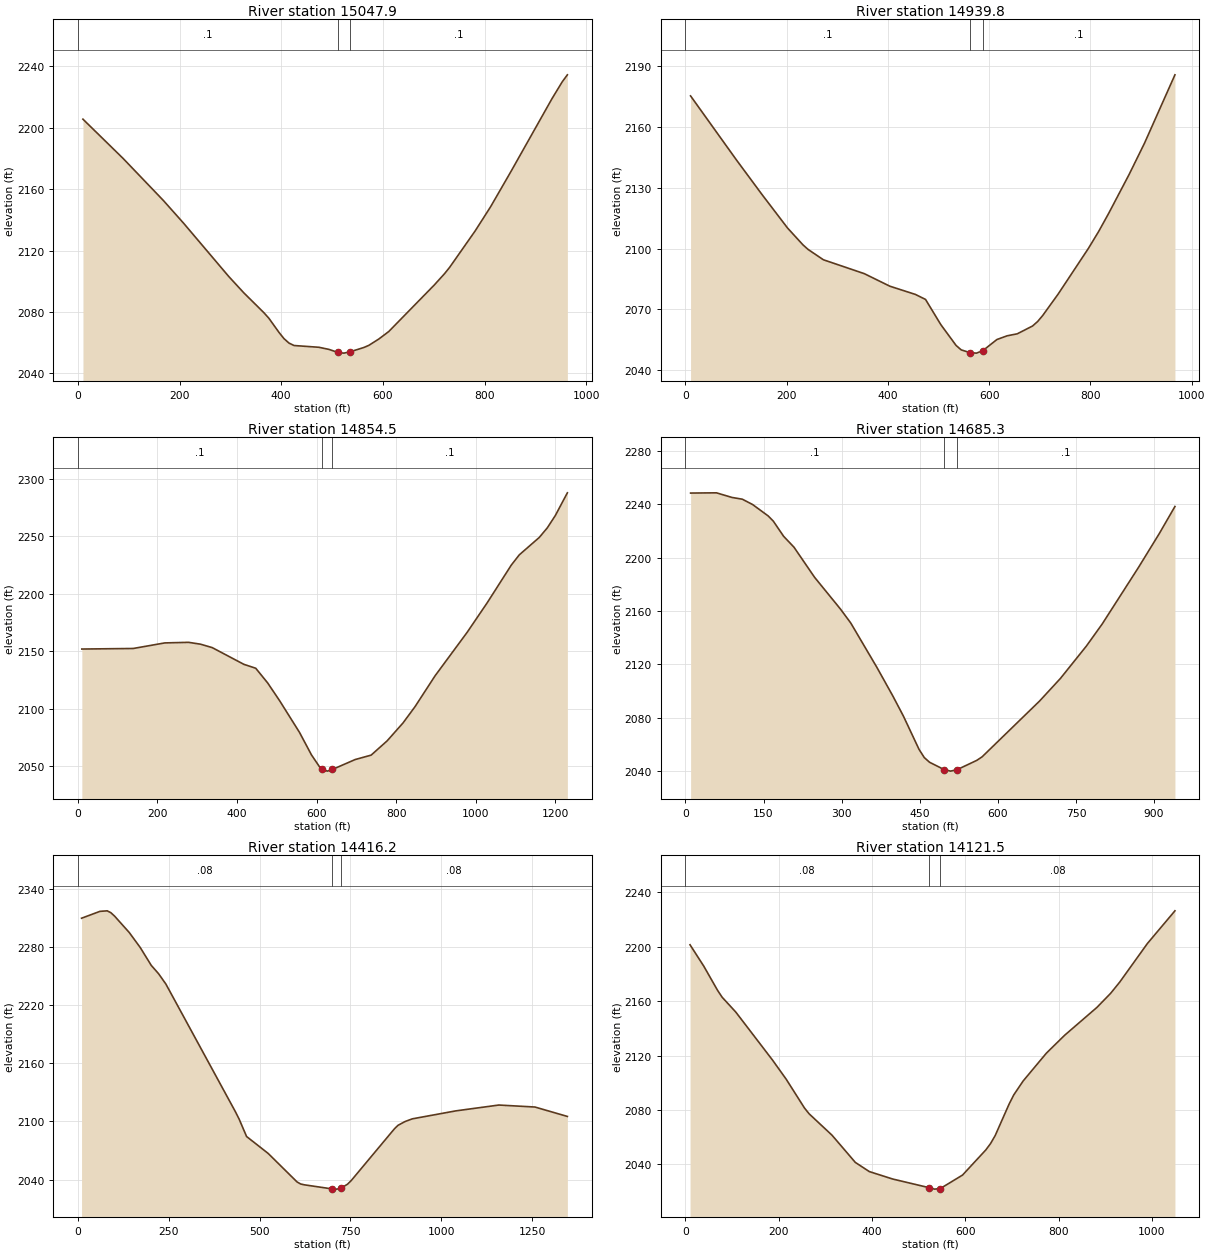
Type RM Length L Ch R = 1 ,15047.9 ,114.9,108.1,101.1
XS GIS Cut Line= 4
     1852252.817      162128.773     1852145.256      162540.034
     1852119.948      162774.136     1852151.583      163074.673
#Sta/Elev= 30
     9.9 2205.63      89 2180.01   168.1 2152.65   207.6 2137.95   296.6 2103.17
   326.2 2092.52   365.8 2079.54   375.7  2075.9   395.4 2066.78   405.3 2062.65
   415.2 2059.74   425.1 2058.14   474.1 2056.99   493.8 2055.62   510.7  2053.7
   523.2 2053.18   535.7 2054.07   562.4 2056.84   572.3 2058.25   591.9 2062.37
   611.5 2067.26   700.9 2097.53     721 2104.87   731.1 2109.01   781.4 2132.79
   811.7  2148.5     852 2171.62   932.5 2218.95   952.7 2229.96   962.8 2234.51
#Mann= 3 , 0 , 0
       0      .1       0   510.7    .045       0   535.7      .1       0
Bank Sta=510.7,535.7
XS Rating Curve= 0 ,0
Exp/Cntr=0.3,0.1

Type RM Length L Ch R = 1 ,14939.8 ,84.9,85.3,86.2
XS GIS Cut Line= 4
     1852183.219      162056.012     1852021.878      162502.072
     1852056.677      162761.482     1852110.457      162986.094
#Sta/Elev= 30
    10.1 2175.45   100.9 2143.74   151.4 2126.66   201.8 2110.14   232.1 2101.86
   242.2  2099.6   272.5 2094.48   353.2 2087.63   403.7 2081.43   454.2 2077.36
   474.3 2074.88   504.5 2062.43   534.7 2052.13   544.8 2049.95   562.5 2048.56
     575 2048.35   587.5 2049.58   615.3 2055.07   635.4  2056.9   655.5 2057.89
   685.7 2061.75   695.8 2063.98   705.9 2066.99   736.1 2077.46   796.3  2100.2
   816.4  2108.5   836.5 2117.59   876.7 2136.74   906.8 2152.04     967 2185.86
#Mann= 3 , 0 , 0
       0      .1       0   562.5    .045       0   587.5      .1       0
Bank Sta=562.5,587.5
XS Rating Curve= 0 ,0
Exp/Cntr=0.3,0.1

Type RM Length L Ch R = 1 ,14854.5 ,168.2,169.1,170.1
XS GIS Cut Line= 4
     1852105.065      162022.864     1851929.478      162433.812
     1851970.573      162781.249      1852146.16      163177.253
#Sta/Elev= 30
     9.9 2151.76     139 2152.24   218.5 2157.09   278.1 2157.59   307.9    2156
   337.6 2152.99   417.1 2138.45   446.9 2135.06   476.9 2122.25   506.9 2106.82
   556.8  2079.3   586.8 2059.76   606.8  2049.5   614.3 2047.14   626.8 2045.58
   639.3 2047.01   696.8 2055.66   736.8 2059.49   776.8 2071.82   816.9 2087.46
   847.1 2101.64   897.5 2128.49   978.1 2166.31  1028.5 2192.01  1088.9 2224.72
    1109 2233.65  1159.4 2248.85  1179.6 2257.21  1199.7 2267.92  1229.9 2287.62
#Mann= 3 , 0 , 0
       0      .1       0   614.3    .045       0   639.3      .1       0
Bank Sta=614.3,639.3
XS Rating Curve= 0 ,0
Exp/Cntr=0.3,0.1

Type RM Length L Ch R = 1 ,14685.3 ,270.4,269.2,267.9
XS GIS Cut Line= 4
     1851883.776       162163.59     1851772.548      162461.003
     1851799.146      162782.596     1851898.284      163065.501
#Sta/Elev= 30
     9.9 2248.36    59.5 2248.54    89.3 2245.08   109.2 2243.76     129 2239.75
   158.8 2231.23   168.7 2227.32   188.5 2215.95   208.4 2207.77   248.1 2185.13
   297.7 2161.35   317.5 2150.88     368  2117.4   398.2 2096.23   418.4 2081.23
   448.6 2056.13   458.7 2049.99   468.8 2046.48   496.6 2041.03   509.1 2039.84
   521.6 2040.92   559.5 2047.91   569.6 2050.53   680.2 2092.46   720.2  2109.4
   770.1 2133.71   800.1 2150.05     870 2192.59     910 2218.02     940  2238.3
#Mann= 3 , 0 , 0
       0      .1       0   496.6    .045       0   521.6      .1       0
Bank Sta=496.6,521.6
XS Rating Curve= 0 ,0
Exp/Cntr=0.3,0.1

Type RM Length L Ch R = 1 ,14416.2 ,262.7,294.7,326.7
XS GIS Cut Line= 4
     1851787.487      162090.305      1851492.38      162448.755
      1851555.89      162930.685     1851634.615      163319.655
#Sta/Elev= 30
    10.1 2309.51    60.6 2316.57    80.7 2317.13    90.8 2315.18   100.9 2311.72
   141.3  2294.8   171.6  2279.3   201.9  2260.9   222.1 2252.26   242.2 2241.61
     434 2109.61   444.1 2102.05   464.3 2084.37   523.8 2066.88   603.2 2037.51
   613.1 2035.39     623 2034.55   699.8 2030.29   712.3 2030.08   724.8 2031.22
   742.1 2035.15     752 2038.76     871 2092.18     881 2095.87   900.8 2099.85
   920.6 2102.58  1039.7 2110.76  1158.7 2116.81    1258 2114.76  1347.3 2105.06
#Mann= 3 , 0 , 0
       0     .08       0   699.8    .045       0   724.8     .08       0
Bank Sta=699.8,724.8
XS Rating Curve= 0 ,0
Exp/Cntr=0.3,0.1

Type RM Length L Ch R = 1 ,14121.5 ,476.8,466.4,456.1
XS GIS Cut Line= 4
     1851554.425      162175.626     1851458.757      162474.907
     1851074.082      162708.165     1850895.731      162931.104
#Sta/Elev= 30
     9.8 2201.39    39.3 2185.67    68.7 2167.98    78.5 2162.91     108  2151.9
   186.6 2116.69     216 2102.59   255.3 2081.39   265.1 2077.18   314.2 2061.46
   364.2 2041.45   394.2 2034.71   444.2 2029.24   521.6 2022.93   534.1  2021.8
   546.6 2022.25   594.1 2032.12   644.1 2050.62   654.1 2055.23   664.1 2061.13
   694.1 2084.38   704.1 2091.12   724.1 2101.28   773.9 2121.72   813.3 2134.95
   882.2 2155.32   911.7  2165.7   931.4 2174.05   990.5  2202.3  1049.6 2226.34
#Mann= 3 , 0 , 0
       0     .08       0   521.6    .045       0   546.6     .08       0
Bank Sta=521.6,546.6
XS Rating Curve= 0 ,0
Exp/Cntr=0.3,0.1

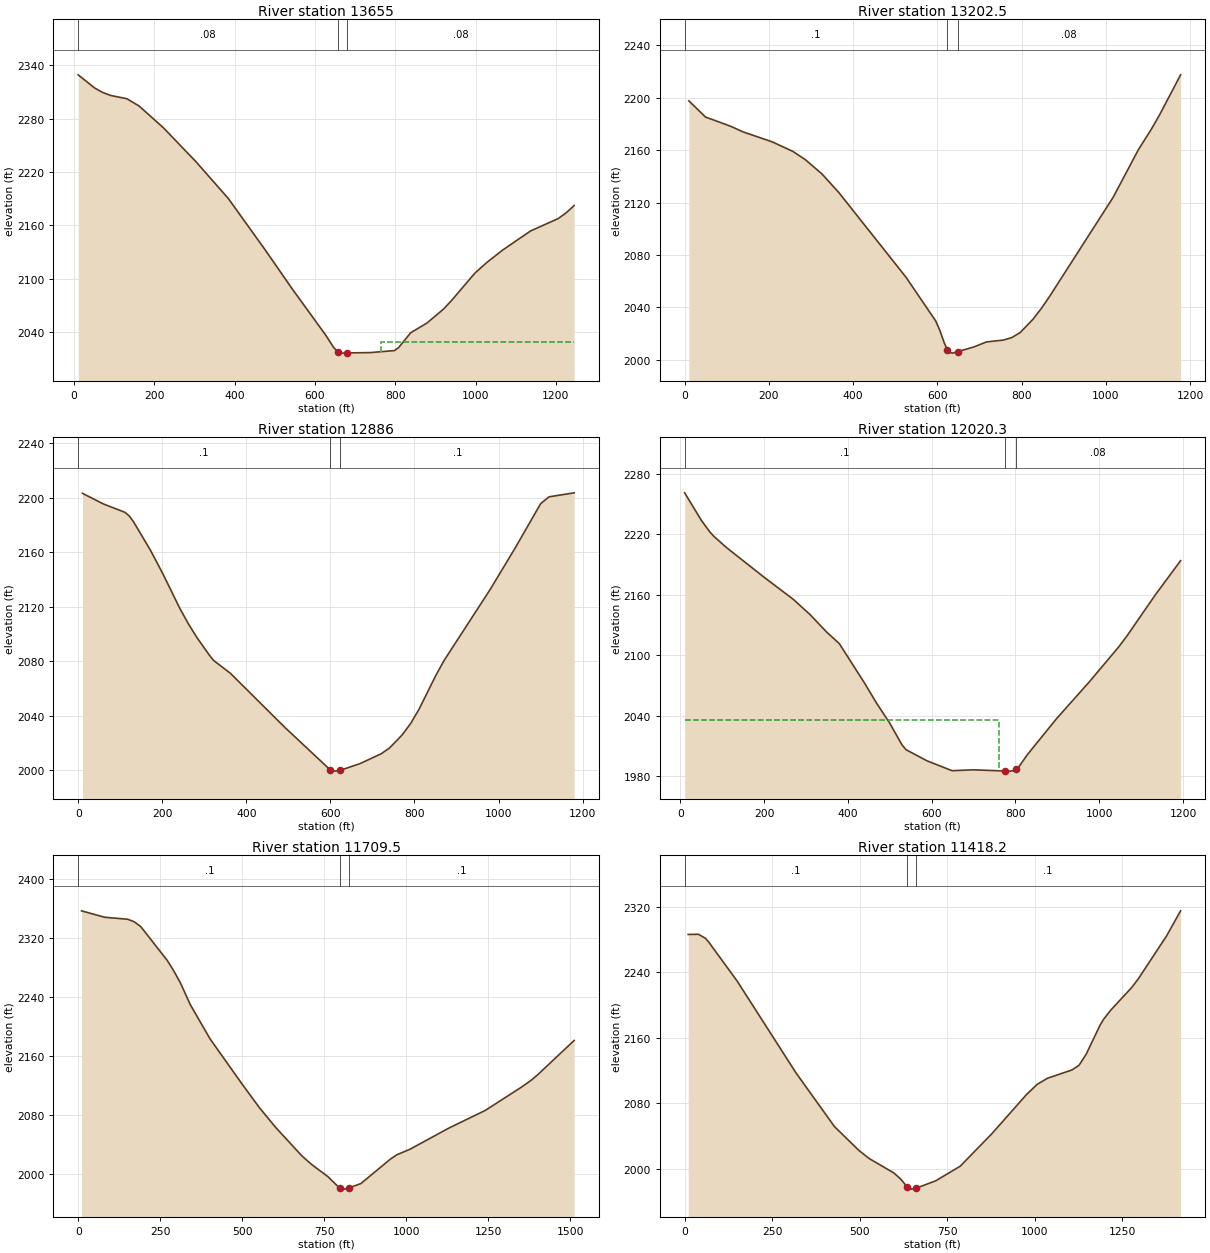
Type RM Length L Ch R = 1 ,13655   ,448.5,452.5,456.6
XS GIS Cut Line= 4
     1851481.742      161848.257     1851138.523      162020.831
     1850806.555      162453.377     1850660.052      162733.643
#Sta/Elev= 30
    10.1 2329.24    50.5  2314.6    70.8 2309.44      91 2306.03   131.4 2302.36
   161.8 2294.16   222.4 2269.65   303.3  2231.6   384.2 2190.07     475 2132.91
   545.7 2086.93   626.5  2036.6   646.7 2022.48   656.8 2017.62   666.9  2016.2
   679.4 2016.43   737.6  2016.8   798.1 2019.07   808.2 2022.36   838.5 2039.14
   878.9 2050.05   919.3 2065.35   939.3 2074.89   998.6 2106.29  1028.2 2118.19
  1067.8 2132.21    1137 2153.58  1206.1 2167.58  1225.9 2174.11  1245.7  2182.2
#Mann= 3 , 0 , 0
    10.1     .08       0   656.8    .045       0   679.4     .08       0
#XS Ineff= 2 , 0
                          763.66         2029.02
Permanent Ineff=
       F       F
Bank Sta=656.8,679.4
XS Rating Curve= 0 ,0
Exp/Cntr=0.3,0.1

Type RM Length L Ch R = 1 ,13202.5 ,317.6,316.5,315.5
XS GIS Cut Line= 4
     1851131.409      161561.621     1850802.059      161780.162
     1850456.222      162115.784      1850296.98      162370.571
#Sta/Elev= 30
     9.9 2197.76    49.4 2185.39   108.7  2178.4   138.3 2174.09   207.5 2166.48
   256.9 2159.16   286.6 2152.83   326.1  2141.9   365.6 2127.92   525.8 2062.99
   596.1 2029.72   606.1 2022.39   616.1 2013.21   623.7 2007.74   626.2 2005.94
   636.2 2005.17   648.7 2006.36   686.4 2009.85   716.5 2013.71   756.7 2015.13
   776.8 2017.03   796.9 2020.94     827 2031.02   847.1 2039.33   867.1 2048.77
  1017.4  2124.1  1077.5 2160.55  1107.5 2175.77  1127.6 2187.02  1177.6  2217.6
#Mann= 3 , 0 , 0
       0      .1       0   623.7    .045       0   648.7     .08       0
Bank Sta=623.7,648.7
XS Rating Curve= 0 ,0
Exp/Cntr=0.3,0.1

Type RM Length L Ch R = 1 ,12886   ,864.7,865.7,866.6
XS GIS Cut Line= 4
     1850887.643       161334.33     1850644.334      161477.425
     1850244.304      161894.862      1850116.91      162187.868
#Sta/Elev= 30
    10.1 2203.14    60.5 2195.25   110.9 2189.24     121 2186.66   131.1  2182.5
   171.4 2161.67   201.6 2144.01   241.9 2118.67   262.1 2107.45   282.3 2097.42
   312.2 2084.39   322.1 2080.58     362 2071.18   491.6 2031.49   598.7 2000.59
   611.2 1999.41   623.7 2000.04     671 2004.98   720.9 2012.16   740.8 2016.41
   770.7 2025.97   790.7 2034.26   810.6 2044.65   850.5 2069.41   870.4 2080.53
   980.2 2132.66  1040.2 2163.36  1100.1  2195.5    1120 2200.55  1179.9 2203.49
#Mann= 3 , 0 , 0
       0      .1       0   598.7    .045       0   623.7      .1       0
Bank Sta=598.7,623.7
XS Rating Curve= 0 ,0
Exp/Cntr=0.3,0.1

Type RM Length L Ch R = 1 ,12020.3 ,305.6,310.9,316.1
XS GIS Cut Line= 4
     1850207.805      161026.567      1849848.59      161148.667
     1849478.737      161525.992     1849303.309      161752.712
#Sta/Elev= 30
      10 2261.35    49.9 2233.94    69.9 2222.62    79.9 2218.04   109.8 2206.99
   199.7 2177.44   269.6 2155.45   309.5  2140.3   349.4 2122.86   379.4 2111.45
   439.2 2072.52   469.1 2051.77     499 2032.98   528.9 2010.96   538.9 2006.01
   588.7 1995.02   648.6  1985.2   698.4 1986.07   775.6 1984.89   788.1 1984.77
   798.1 1985.57   800.6 1986.43   808.1    1989     828 2000.92   897.8 2036.76
     977  2073.8  1046.1 2108.01  1065.9 2118.94  1135.1  2160.6  1194.4 2193.94
#Mann= 3 , 0 , 0
      10      .1       0   775.6    .045       0   800.6     .08       0
#XS Ineff= 2 , 0
          760.48 2035.85
Permanent Ineff=
       F       F
Bank Sta=775.6,800.6
XS Rating Curve= 0 ,0
Exp/Cntr=0.3,0.1

Type RM Length L Ch R = 1 ,11709.5 ,284,291.3,298.6
XS GIS Cut Line= 4
     1850201.435      160816.368     1849768.296      160905.543
     1849261.604      161244.291     1848984.825      161612.578
#Sta/Elev= 30
    10.1  2356.2    80.4 2347.52   150.8 2344.77   170.9 2341.35     191 2334.74
   271.4 2289.07   291.5  2274.7   311.6 2258.63   341.7 2229.14     402 2182.72
   502.2 2119.91   552.1 2089.69   602.1 2062.69     682 2024.12     712 2012.38
     762 1995.76   791.9 1982.67   799.4 1980.36   811.9 1979.01   824.4 1980.51
   861.9 1986.51   951.8 2019.59   971.8 2025.59  1011.8 2033.06  1131.8 2062.07
    1242 2085.84  1352.2 2117.41  1382.2 2126.85  1402.3 2134.45  1512.4 2180.52
#Mann= 3 , 0 , 0
       0      .1       0   799.4    .045       0   824.4      .1       0
Bank Sta=799.4,824.4
XS Rating Curve= 0 ,0
Exp/Cntr=0.3,0.1

Type RM Length L Ch R = 1 ,11418.2 ,213.6,221.2,228.8
XS GIS Cut Line= 4
     1849959.387      160720.822     1849612.883      160755.952
        1849074.      160937.392     1848710.928      161281.355
#Sta/Elev= 30
      10 2286.36    39.8 2286.49    59.7  2281.5    69.7 2276.43   149.3 2229.74
   318.4 2116.84   428.1 2051.33   497.9 2022.15   527.8 2012.13   597.7 1994.68
   617.6 1987.04     635 1978.03   647.5 1974.88     660  1975.8   717.4 1985.09
   787.2 2002.91     877 2042.32   976.9 2090.67  1006.9 2102.91  1036.9 2110.54
  1106.9 2120.67  1126.9 2126.44  1146.9 2139.65    1187 2175.45    1197 2182.62
    1217 2193.56    1277 2221.34    1297  2232.6    1377  2284.6    1417 2315.21
#Mann= 3 , 0 , 0
       0      .1       0     635    .045       0     660      .1       0
Bank Sta=635,660
XS Rating Curve= 0 ,0
Exp/Cntr=0.3,0.1