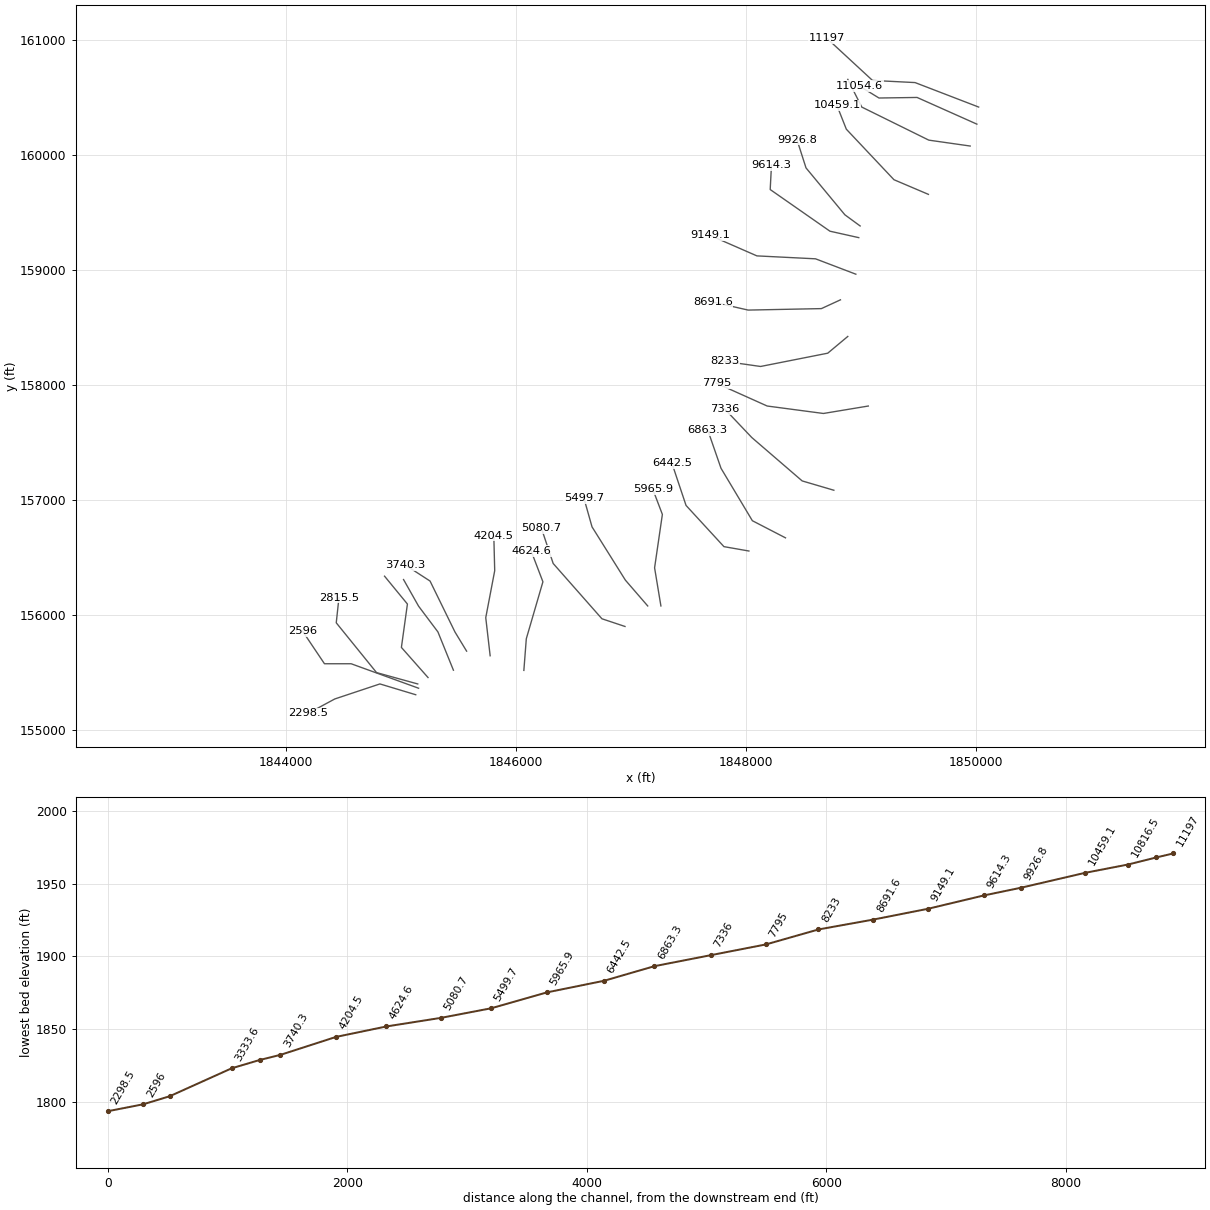
HEC-RAS study Buzzard Branch.prj: Buzzard Branch

--- Buzzard Branch.g01 (geometry) --- (continued)

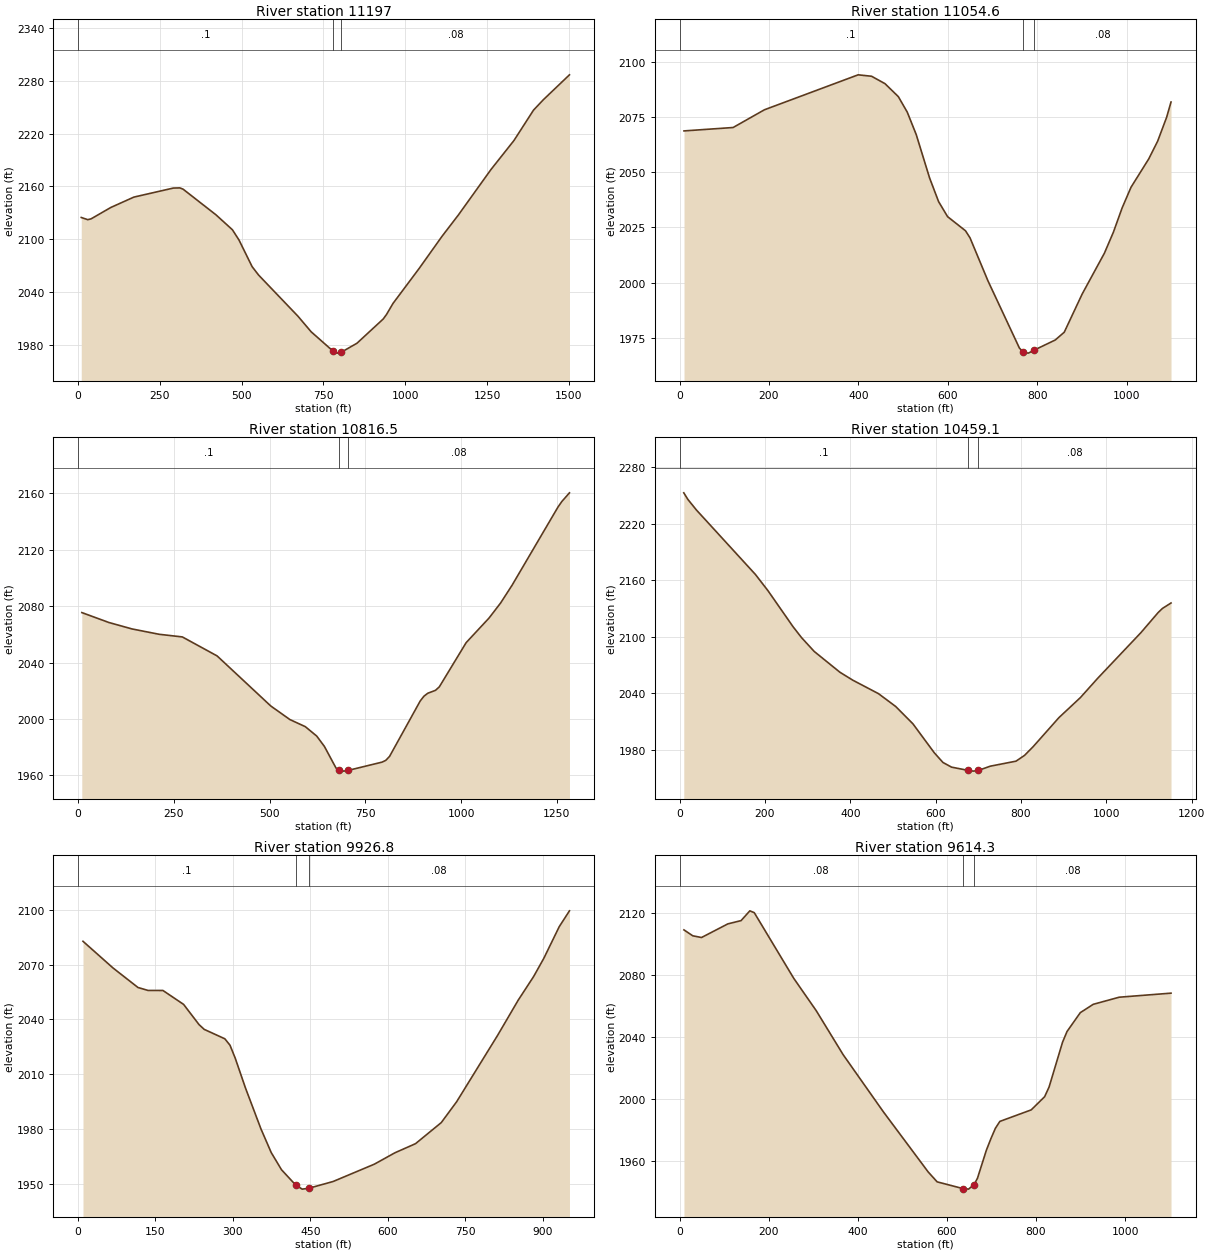
Type RM Length L Ch R = 1 ,11197   ,140.6,142.4,144.2
XS GIS Cut Line= 4
     1850020.441      160416.433     1849467.529      160629.379
     1849097.677      160648.058     1848701.673      161014.175
#Sta/Elev= 30
      10 2124.82    30.1 2122.31    40.2 2123.27   100.4 2136.19   170.7 2147.94
   291.2 2158.21   311.3 2158.42   321.4 2156.93   421.8 2127.81     472 2110.85
   492.1 2099.23   532.2 2068.97   552.3 2059.29   672.6 2012.55   712.6 1994.99
   780.2 1972.81   792.7 1970.75   805.2 1971.88   852.7    1982   932.8 2009.48
   942.8 2014.55   962.8 2027.19  1042.7 2066.92  1112.6 2103.42  1162.6 2127.67
  1262.4 2179.37  1332.4  2212.2  1392.3 2246.76  1422.2 2258.52  1502.1 2286.83
#Mann= 3 , 0 , 0
       0      .1       0   780.2    .045       0   805.2     .08       0
Bank Sta=780.2,805.2
XS Rating Curve= 0 ,0
Exp/Cntr=0.3,0.1

Type RM Length L Ch R = 1 ,11054.6 ,252.3,238.1,223
XS GIS Cut Line= 4
     1850004.996      160267.884     1849485.127      160500.012
     1849153.862      160495.176     1848984.603      160599.149
#Sta/Elev= 30
      10 2068.73   119.9 2070.28   189.8 2078.31   399.5 2094.16   429.5 2093.51
   459.5 2090.16   489.4 2084.27   509.4 2077.22   529.4 2067.07   559.3  2047.4
   579.4 2036.69   599.5 2029.87   639.6 2023.46   649.7 2020.26   689.8 2000.78
   760.1 1970.33   767.7 1968.58   780.2 1967.99   792.7  1969.3   840.4 1973.95
   860.5 1977.48   900.6  1994.8   950.3  2013.3   970.2 2022.71     990 2033.86
  1009.9 2043.22  1049.6 2056.09  1069.5 2064.13  1089.4 2074.87  1099.3 2081.83
#Mann= 3 , 0 , 0
       0      .1       0   767.7    .045       0   792.7     .08       0
Bank Sta=767.7,792.7
XS Rating Curve= 0 ,0
Exp/Cntr=0.3,0.1

Type RM Length L Ch R = 1 ,10816.5 ,367.2,357.4,348.5
XS GIS Cut Line= 4
     1849946.647      160077.484     1849587.078       160128.77
      1849004.28      160416.433      1848882.91      160657.125
#Sta/Elev= 30
    10.1 2075.37    80.7 2068.35   141.2 2063.78   211.9    2060   272.4 2058.13
   363.2 2044.66   503.2 2009.22   553.2 1999.59   593.2  1994.6   623.2 1987.89
   643.2 1980.55   673.2 1965.39   680.7 1963.69   693.2 1963.09   705.7 1963.65
   793.2 1969.43   803.2 1970.69   813.2 1973.53   893.1 2012.73   903.1 2016.21
   913.1 2018.27   933.1 2020.32   943.1  2022.8  1013.1  2054.1    1073 2071.57
    1103 2082.17  1132.9 2094.73  1252.7 2150.09  1262.7 2154.01  1282.7 2160.19
#Mann= 3 , 0 , 0
       0      .1       0   680.7    .045       0   705.7     .08       0
Bank Sta=680.7,705.7
XS Rating Curve= 0 ,0
Exp/Cntr=0.3,0.1

Type RM Length L Ch R = 1 ,10459.1 ,534.7,532.2,529.1
XS GIS Cut Line= 4
     1849583.575      159657.084       1849284.2      159784.478
      1848870.17      160223.987     1848788.407      160430.772
#Sta/Elev= 30
     9.9 2252.71    19.7 2245.62    39.4 2234.56   177.5 2166.23     207 2148.98
   266.2 2110.47   285.9 2099.03   315.5 2084.41   375.7 2062.35   405.9 2053.91
   466.2 2039.58   506.5 2025.96   546.8 2007.59   597.1 1976.74   617.2 1966.57
   637.3 1961.63   675.1 1958.26   687.6  1957.4   700.1 1958.12   727.9 1962.63
   788.3 1967.97   808.4 1974.15   828.5 1983.36   888.9 2014.18   939.3  2035.5
   979.7 2055.92  1080.8 2104.27  1121.2 2125.59  1131.3    2130  1151.5 2135.81
#Mann= 3 , 0 , 0
       0      .1       0   675.1    .045       0   700.1     .08       0
Bank Sta=675.1,700.1
XS Rating Curve= 0 ,0
Exp/Cntr=0.3,0.1

Type RM Length L Ch R = 1 ,9926.8  ,304.9,312.6,320.3
XS GIS Cut Line= 4
     1848990.196      159382.235     1848857.421      159479.595
     1848519.782      159887.222     1848441.021      160133.148
#Sta/Elev= 30
     9.7 2082.74    67.8 2068.17   116.2 2057.48   135.6 2055.87   164.6 2055.84
   204.6 2048.24   234.6 2037.16   244.5 2034.58   284.5 2029.43   294.5 2025.92
   304.5 2018.94   324.4  2002.6   354.4 1980.21   374.4 1967.19   394.3 1957.82
   421.8 1949.45   434.3 1947.22   446.8 1947.66   494.2 1951.38   574.1 1960.85
   614.1  1967.1     654 1972.08   703.9 1983.62   733.7 1995.04   813.1 2031.36
   852.9 2050.55   882.7 2063.44   902.5 2073.42   932.3 2090.69   952.2  2099.4
#Mann= 3 , 0 , 0
       0      .1       0   421.8    .045       0   446.8     .08       0
Bank Sta=421.8,446.8
XS Rating Curve= 0 ,0
Exp/Cntr=0.3,0.1

Type RM Length L Ch R = 1 ,9614.3  ,449.5,465.1,480.8
XS GIS Cut Line= 4
     1848978.128      159280.724     1848727.824      159336.762
     1848208.536      159699.143     1848219.744      159912.089
#Sta/Elev= 30
     9.9 2108.87    29.6 2105.07    49.3 2103.96   108.5 2112.75   138.1 2114.85
   157.8 2121.15   167.7 2119.95   256.5 2077.58   306.8 2056.81   367.1 2028.51
   457.5 1991.65     558 1952.95   578.1 1946.57     636 1942.23   648.5 1941.88
     661 1944.77   668.6 1948.88   688.7 1967.04   698.8 1974.39   708.8 1981.06
   718.9 1985.51   789.2 1992.92   819.4 2001.43   829.4 2007.71   859.6 2036.57
   869.6 2043.41   899.4 2055.56   928.5 2060.93   986.7 2065.51    1103 2068.12
#Mann= 3 , 0 , 0
       0     .08       0     636    .045       0     661     .08       0
Bank Sta=636,661
XS Rating Curve= 0 ,0
Exp/Cntr=0.3,0.1

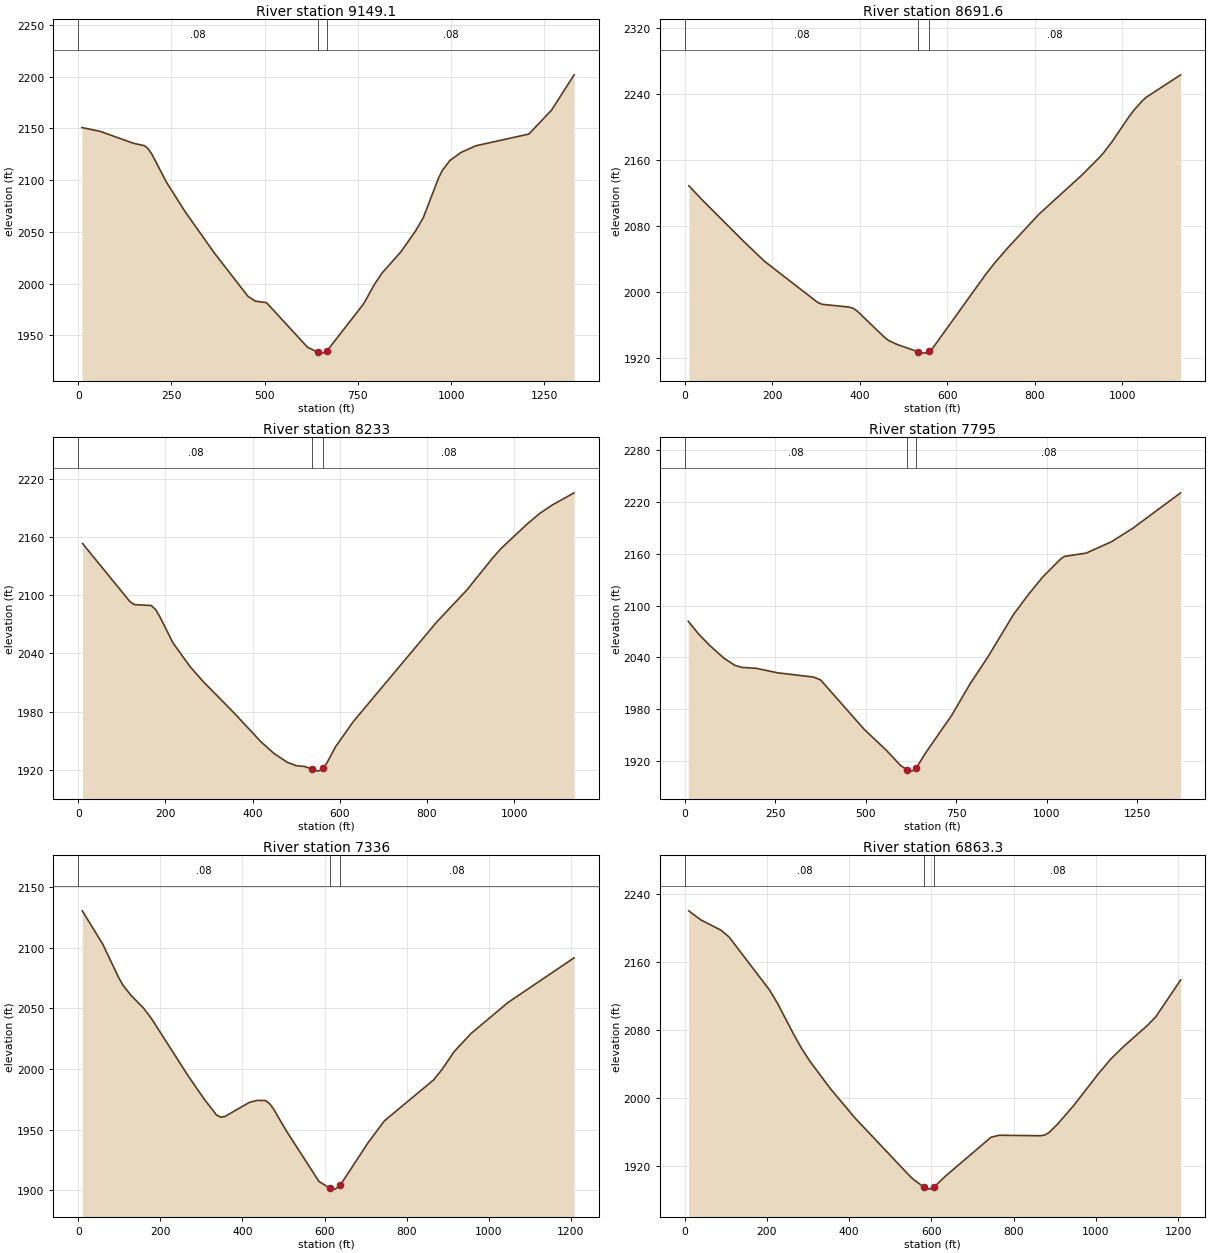
Type RM Length L Ch R = 1 ,9149.1  ,455.6,457.5,459.4
XS GIS Cut Line= 4
     1848952.976      158962.788     1848602.643      159096.552
     1848093.068      159122.031     1847685.408      159300.382
#Sta/Elev= 30
     9.9 2150.76    59.2 2147.07     148  2135.6   177.6 2133.25   187.5 2130.39
   197.4 2125.13   236.8 2097.93   286.2 2069.75   365.1 2029.56     455 1987.76
     475 1982.99   505.1 1981.52   615.1 1938.43   642.6 1933.62   655.1 1932.74
   667.6 1935.09   765.2 1980.22   795.2 1999.56   815.2 2010.29   865.2 2030.52
   905.4 2051.12   925.7 2063.77   966.1 2101.66   976.2 2109.04   996.5 2118.79
  1026.8 2126.77  1067.2 2133.22  1208.8  2144.5  1269.5 2167.59  1330.2 2201.74
#Mann= 3 , 0 , 0
       0     .08       0   642.6    .045       0   667.6     .08       0
Bank Sta=642.6,667.6
XS Rating Curve= 0 ,0
Exp/Cntr=0.3,0.1

Type RM Length L Ch R = 1 ,8691.6  ,453.9,458.7,463.5
XS GIS Cut Line= 4
     1848819.213      158739.849     1848653.504      158663.509
     1848016.632      158650.674     1847710.887       158720.74
#Sta/Elev= 30
     9.6 2128.24    38.4 2111.97   134.4 2061.02   182.4 2036.68   303.8 1986.81
   313.9 1984.52   374.6 1981.18   384.7 1979.81   394.8 1976.04   455.4 1945.07
   465.6 1940.69   485.8 1935.74   533.9 1926.79   546.4 1925.31   556.6 1926.24
   558.9 1927.41   566.7 1931.35     688 2020.94   708.2 2034.54   738.6 2053.19
   809.3 2093.74   907.7 2141.29   946.9 2162.21   956.7 2168.05   976.3 2181.61
  1015.5 2212.22  1025.3 2219.12  1044.9 2230.87  1054.7 2235.62  1133.1 2262.76
#Mann= 3 , 0 , 0
       0     .08       0   533.9    .045       0   558.9     .08       0
Bank Sta=533.9,558.9
XS Rating Curve= 0 ,0
Exp/Cntr=0.3,0.1

Type RM Length L Ch R = 1 ,8233    ,446.9,437.9,428.9
XS GIS Cut Line= 4
      1848882.91      158421.365     1848708.669      158275.808
     1848124.917      158160.208     1847812.802      158204.796
#Sta/Elev= 30
     9.9 2153.54   118.5  2093.6   128.3  2090.5   167.8 2089.46   177.7  2085.2
   187.6 2077.61   217.2    2051   257.3 2025.93   287.6 2010.55   358.2 1978.25
   418.7    1949   448.9 1936.78   479.2 1927.69   499.4  1924.2   519.5 1923.26
   537.3 1920.51   549.8 1918.51   559.9 1920.17   562.3 1921.72     570  1926.7
   590.1 1943.61   630.5 1969.43   822.1 2072.43   891.1 2105.38   950.2  2138.4
   969.9 2148.43    1029 2173.38  1058.6 2184.63  1088.1 2193.52  1137.4 2205.84
#Mann= 3 , 0 , 0
       0     .08       0   537.3    .045       0   562.3     .08       0
Bank Sta=537.3,562.3
XS Rating Curve= 0 ,0
Exp/Cntr=0.3,0.1

Type RM Length L Ch R = 1 ,7795    ,475.1,459,443
XS GIS Cut Line= 4
     1849061.261      157816.245     1848671.117      157751.426
     1848182.244      157816.245     1847742.736      158013.705
#Sta/Elev= 30
     9.9 2081.96    39.5 2066.72    69.2 2053.92   108.8 2039.05   138.4 2030.95
   158.2 2028.45   197.7 2027.41   257.1 2022.19   355.9 2017.28   375.7 2013.94
   496.1 1956.66   556.5 1932.74   596.8 1914.74   614.5 1909.92     627 1908.24
     637 1909.93   639.5  1911.5   667.2 1930.22   737.7 1972.77     788 2008.92
   838.3 2040.86   908.7 2089.81   948.9 2112.45     989  2133.1  1039.2 2154.21
  1049.3  2157.1  1109.5 2160.97  1179.7 2174.21    1240 2190.25  1370.5 2230.85
#Mann= 3 , 0 , 0
       0     .08       0   614.5    .045       0   639.5     .08       0
Bank Sta=614.5,639.5
XS Rating Curve= 0 ,0
Exp/Cntr=0.3,0.1

Type RM Length L Ch R = 1 ,7336    ,481.5,472.7,463.9
XS GIS Cut Line= 4
     1848761.886      157083.731      1848486.47      157164.776
     1848048.481      157542.348     1847812.802      157790.766
#Sta/Elev= 30
     9.9 2130.54    59.4 2103.27      99 2075.17   108.9 2069.22   128.7 2060.73
   158.4 2050.54   178.2 2041.74   267.3 1994.58     307 1975.07   336.9    1962
   346.9 1960.28   356.9 1960.75   416.7 1972.43   436.6 1974.16   456.6 1973.91
   466.6 1971.19   476.5 1966.61   506.4  1949.2   586.2 1907.27   613.6 1901.47
   626.1 1900.88   638.6  1904.4   705.8 1939.09   745.7 1957.24   865.4 1990.97
   885.5 1999.38   915.7 2014.38     956 2029.09  1046.6 2054.88  1207.8 2091.77
#Mann= 3 , 0 , 0
       0     .08       0   613.6    .045       0   638.6     .08       0
Bank Sta=613.6,638.6
XS Rating Curve= 0 ,0
Exp/Cntr=0.3,0.1

Type RM Length L Ch R = 1 ,6863.3  ,416.1,420.8,425.5
XS GIS Cut Line= 4
     1848341.486      156669.701     1848053.492      156818.722
     1847780.954      157274.821     1847666.299      157606.045
#Sta/Elev= 30
     9.8 2220.32    39.3 2209.67    88.4 2197.58   108.1  2189.5   206.4 2127.26
     226 2111.45   265.3    2075     285  2058.1   304.6 2043.58   354.3 2011.39
   414.5 1976.74   544.8 1910.07   554.8 1905.23   582.4 1895.48   594.9 1893.29
   607.4 1896.17     635 1908.89   745.3 1954.36   765.4 1956.62   865.6 1956.01
   875.6 1956.85   885.6 1959.57   905.7  1969.1   945.7 1991.28  1005.8 2028.72
  1035.8 2045.89  1065.9 2060.24    1126 2085.97    1146 2095.96  1206.1 2139.05
#Mann= 3 , 0 , 0
       0     .08       0   582.4    .045       0   607.4     .08       0
Bank Sta=582.4,607.4
XS Rating Curve= 0 ,0
Exp/Cntr=0.3,0.1

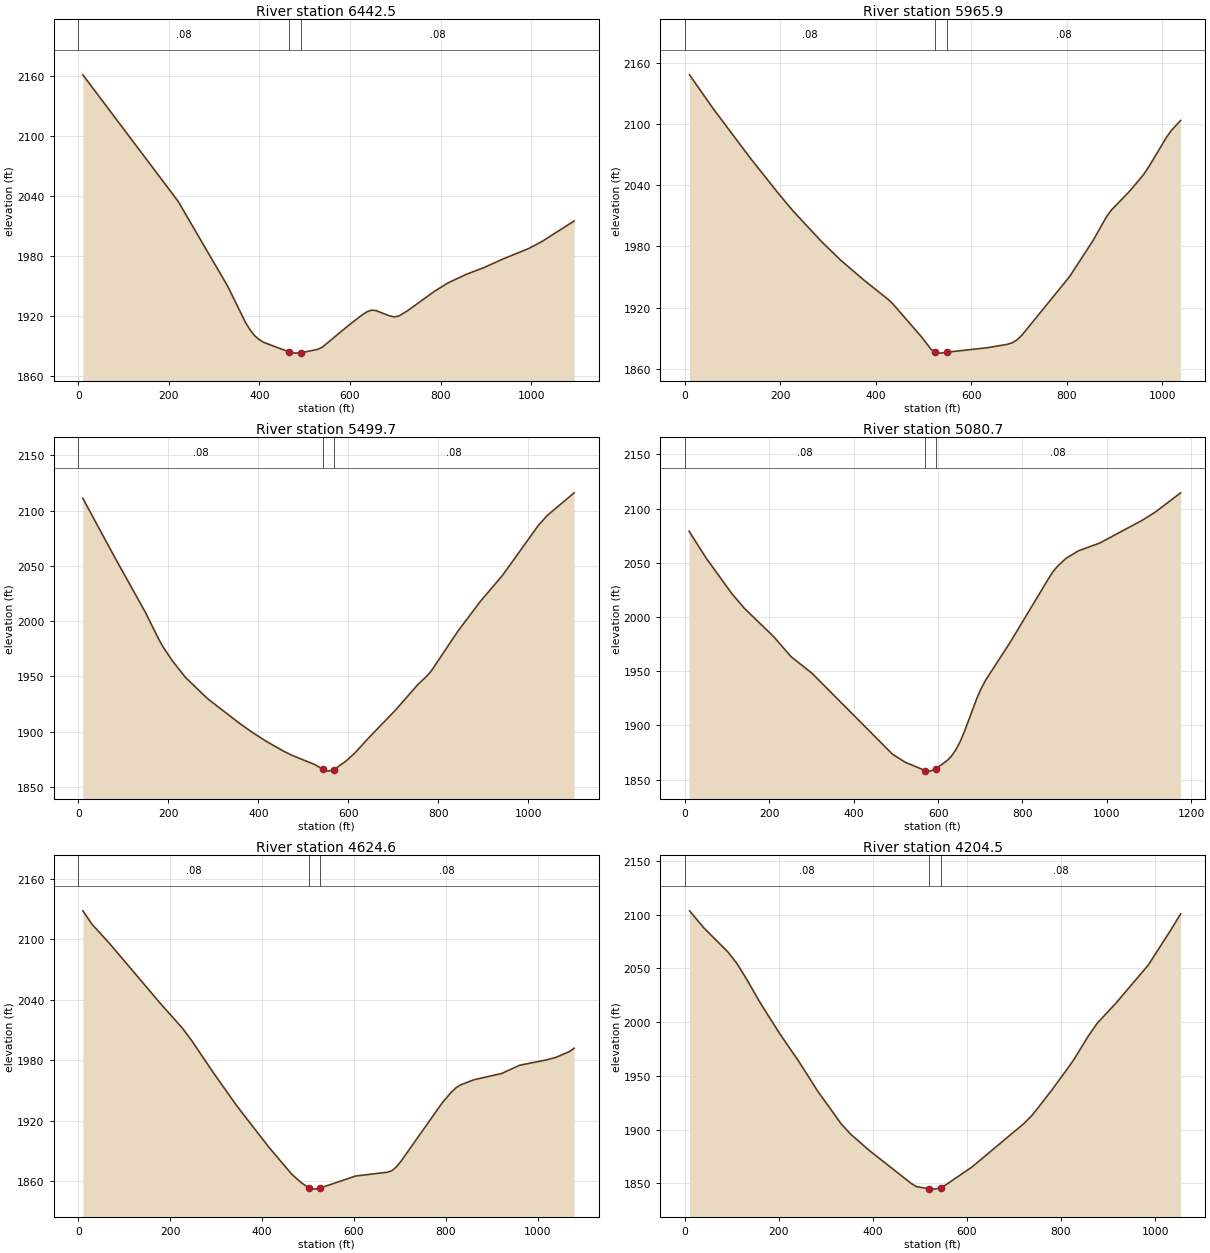
Type RM Length L Ch R = 1 ,6442.5  ,500.3,476.6,452.8
XS GIS Cut Line= 4
     1848023.599      156555.098     1847806.432      156593.265
     1847477.042      156951.652     1847354.185      157319.409
#Sta/Elev= 30
      10 2161.41   220.5  2034.9   329.8 1950.13   369.5 1913.68   379.4 1906.38
   389.4 1900.66   399.3 1896.77   409.2 1894.03   466.3 1884.33   478.8 1883.25
   491.3 1883.59   528.4 1886.99   538.4 1889.07     598 1911.38   627.8 1921.81
   637.7 1924.62   647.7 1926.19   657.6 1925.75   687.4 1920.49   697.3 1919.51
   707.3 1920.18   727.1  1925.6   786.8 1945.13   816.6 1953.47   856.4 1961.97
   896.2  1968.8   935.9 1976.99   995.6 1987.98  1025.4 1995.24    1095 2015.36
#Mann= 3 , 0 , 0
       0     .08       0   466.3    .045       0   491.3     .08       0
Bank Sta=466.3,491.3
XS Rating Curve= 0 ,0
Exp/Cntr=0.3,0.1

Type RM Length L Ch R = 1 ,5965.9  ,445.7,466.3,486.8
XS GIS Cut Line= 4
     1847258.639       156077.32     1847203.707      156409.102
     1847271.379      156873.531     1847188.532      157091.231
#Sta/Elev= 30
     9.9 2148.15    59.3 2115.11   138.5 2065.74   197.8 2030.85   227.5 2014.29
   286.8 1984.47   326.4 1966.46   376.2 1946.52   426.2 1927.91   436.2 1923.38
   496.1 1891.11     516 1878.93   523.5 1876.53     536 1875.29   548.5 1876.15
   635.9 1880.73   675.8 1883.93   685.8 1885.41   695.8 1888.26   705.8 1892.71
   805.6 1950.07   854.2 1984.93   883.3 2008.99     893 2015.27   931.8 2034.08
   960.9  2050.3   970.6 2056.96  1009.4 2087.16  1019.2 2093.62  1038.6 2103.41
#Mann= 3 , 0 , 0
       0     .08       0   523.5    .045       0   548.5     .08       0
Bank Sta=523.5,548.5
XS Rating Curve= 0 ,0
Exp/Cntr=0.3,0.1

Type RM Length L Ch R = 1 ,5499.7  ,414.5,419,423.5
XS GIS Cut Line= 4
     1847143.985       156077.32     1846949.768      156302.035
     1846659.889      156765.246     1846589.822      157013.664
#Sta/Elev= 30
     9.9  2111.2    79.2 2059.01   148.5 2008.35   178.2 1984.09   188.1 1976.84
   207.9 1964.71   237.6  1949.3   287.1 1929.91   356.6  1908.1   386.4 1899.44
   416.2 1891.67     456 1882.41   475.8 1878.47   525.5 1870.29   542.8 1866.13
   555.3 1864.36   567.8 1865.61   595.1 1873.62   614.9 1880.99   644.7 1894.28
   704.4 1919.47     754 1942.53   773.9  1950.2   783.8 1954.75   843.5 1991.05
   893.1 2017.83   942.7 2041.59  1022.1 2086.64    1042 2095.68  1101.6 2116.08
#Mann= 3 , 0 , 0
       0     .08       0   542.8    .045       0   567.8     .08       0
Bank Sta=542.8,567.8
XS Rating Curve= 0 ,0
Exp/Cntr=0.3,0.1

Type RM Length L Ch R = 1 ,5080.7  ,483.6,456.1,428.5
XS GIS Cut Line= 4
     1846946.525      155898.969     1846746.017       155965.86
     1846322.295      156446.762      1846220.38      156752.507
#Sta/Elev= 30
    10.1 2079.12    50.3 2054.48   110.7 2021.94   140.9 2008.06   211.4 1981.51
   251.4 1963.49   301.5 1948.02   491.8 1873.49   521.8 1866.06   569.4  1858.3
   581.9 1857.78   594.4 1859.79     622  1867.7     632 1871.78     642 1877.45
     652 1884.72     662 1893.87   692.1 1925.11   702.1 1933.93   712.1 1941.34
   772.2 1977.48   862.4 2035.84   872.5 2041.94   882.5 2046.54   902.7 2053.98
   932.9 2061.09   983.2 2068.23    1084 2089.26  1114.2 2096.64  1174.6 2114.52
#Mann= 3 , 0 , 0
       0     .08       0   569.4    .045       0   594.4     .08       0
Bank Sta=569.4,594.4
XS Rating Curve= 0 ,0
Exp/Cntr=0.3,0.1

Type RM Length L Ch R = 1 ,4624.6  ,417.4,420.2,422.9
XS GIS Cut Line= 4
     1846067.508      155516.788     1846088.728      155791.976
      1846233.12       156287.52     1846130.604      156555.856
#Sta/Elev= 30
     9.9 2128.21    29.6 2114.99      69 2095.26   177.4 2036.91   226.7 2011.64
   246.4  1999.6   295.9 1966.21   345.5 1934.28     415 1893.38   464.6 1866.71
   484.5 1858.56   501.7 1853.19   514.2 1851.87   526.7    1853   603.6 1864.89
     673 1868.68     683 1870.28   692.9 1874.18   702.8 1879.78   792.2 1937.57
     812 1948.11   821.9 1952.44   831.8 1955.29   861.5 1960.52   920.9 1966.59
   960.5 1974.84    1020 1980.24  1039.8 1982.73  1069.5 1988.52  1079.4  1991.8
#Mann= 3 , 0 , 0
       0     .08       0   501.7    .045       0   526.7     .08       0
Bank Sta=501.7,526.7
XS Rating Curve= 0 ,0
Exp/Cntr=0.3,0.1

Type RM Length L Ch R = 1 ,4204.5  ,446.3,464.1,482
XS GIS Cut Line= 4
     1845774.502      155644.181     1845736.284      155975.405
     1845814.113      156384.013     1845806.351       156688.81
#Sta/Elev= 30
    10.1 2103.42    40.4 2087.63    90.9 2065.57   111.1 2054.32   131.3 2040.02
   161.7 2016.93   202.1 1989.09   242.5 1963.37   282.9 1935.63   333.4 1904.88
   353.2 1895.59   392.8 1880.46     482 1849.83   491.9 1847.15     519 1844.95
   531.5 1844.69     544 1846.02   551.3 1847.58   610.7 1865.28   719.7 1905.13
   739.5  1913.8   778.9 1935.91   818.2 1959.41   828.1 1965.63   857.6 1986.76
   877.2 1999.03   916.6 2017.55   985.4 2052.93  1034.6  2086.4  1054.3 2100.56
#Mann= 3 , 0 , 0
       0     .08       0     519    .045       0     544     .08       0
Bank Sta=519,544
XS Rating Curve= 0 ,0
Exp/Cntr=0.3,0.1

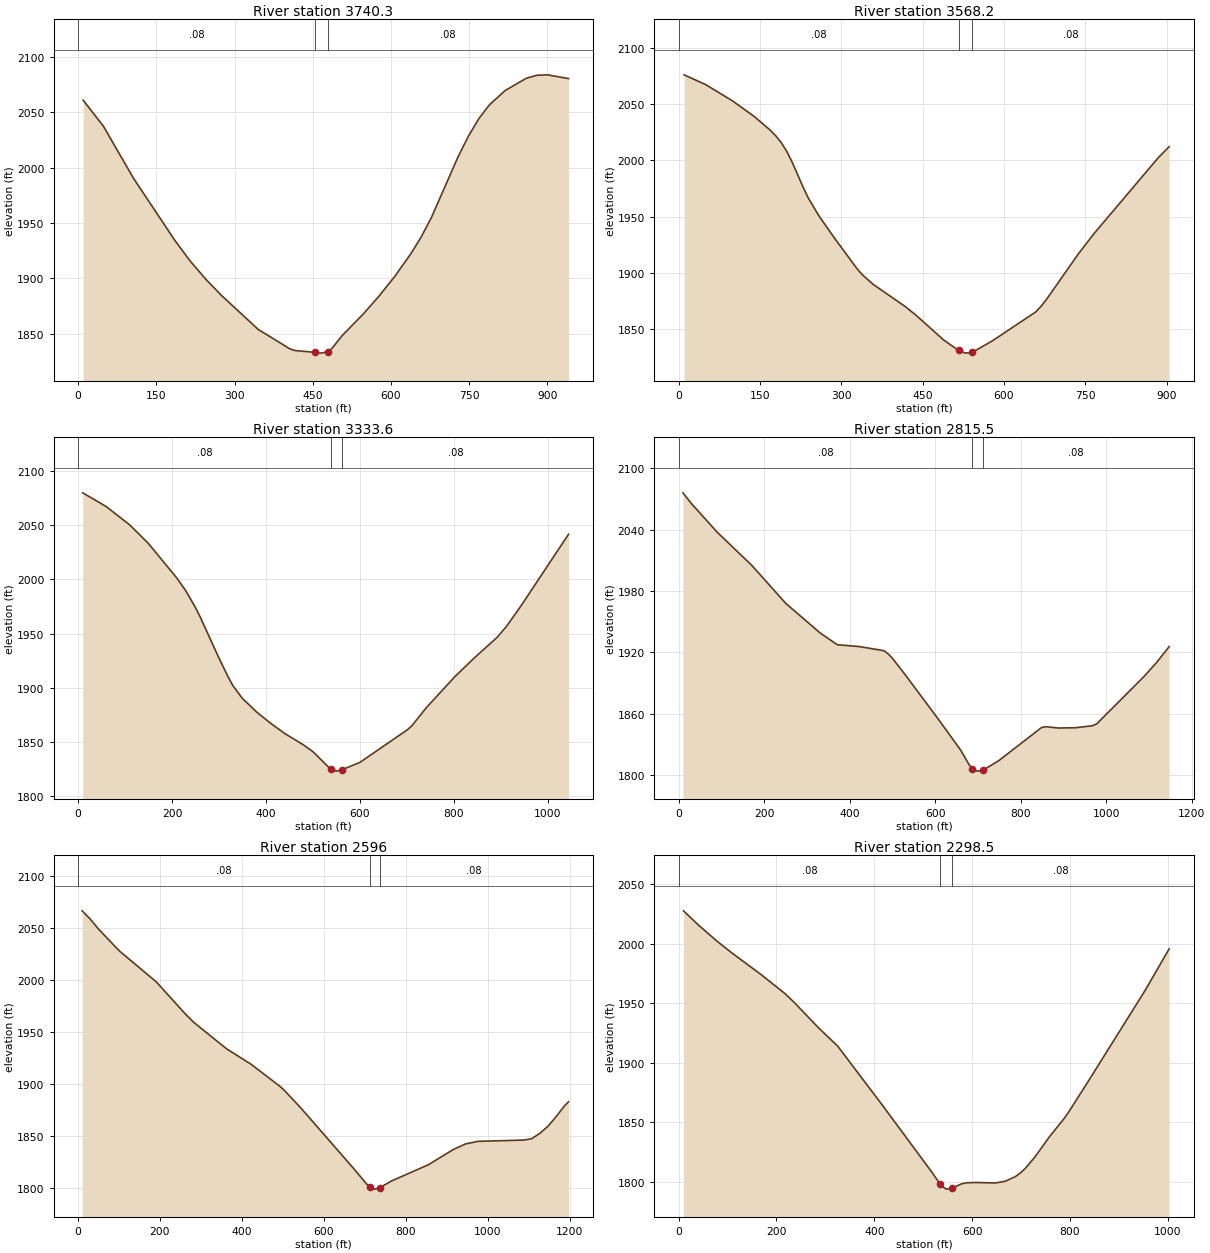
Type RM Length L Ch R = 1 ,3740.3  ,166.8,172.2,177
XS GIS Cut Line= 4
     1845569.866      155684.377     1845468.883      155850.587
     1845252.188      156293.889     1845040.187      156431.404
#Sta/Elev= 30
     9.7 2060.98    48.6 2037.44     107 1989.85   184.8 1934.79   214.6 1915.84
   244.8 1899.25     275 1884.49   345.5 1853.77     406 1836.27     416 1834.72
   453.9 1833.06   466.4 1832.36   478.9 1833.66   486.5 1836.44   506.7 1848.32
   546.9 1867.72   577.1 1883.85   607.4 1901.73   637.6  1921.8   657.7 1937.05
   677.8 1955.09   728.3 2009.34   748.6 2028.44   768.8 2044.45     789  2056.8
   819.3 2069.75   859.7 2080.79     880 2083.46   900.2 2083.86   940.6 2080.48
#Mann= 3 , 0 , 0
       0     .08       0   453.9    .045       0   478.9     .08       0
Bank Sta=453.9,478.9
XS Rating Curve= 0 ,0
Exp/Cntr=0.3,0.1

Type RM Length L Ch R = 1 ,3568.2  ,256.6,234.6,212.8
XS GIS Cut Line= 4
     1845455.188      155518.687     1845320.696      155851.181
     1845152.581      156075.334     1845021.825      156306.959
#Sta/Elev= 30
      10 2075.86    49.8 2067.19    99.6 2052.67   139.5 2038.87   169.4 2026.53
   179.3  2021.6   189.3 2015.63   199.3 2008.02   209.2 1998.54   229.1 1976.75
   239.1 1966.52     259 1950.51   288.9    1930   328.8 1903.96   338.7 1898.47
   358.7 1889.95   418.7 1869.93   438.7 1862.14   488.8 1840.55   516.3 1831.25
   528.8 1828.86   541.3 1829.46   578.8 1839.79   658.6 1865.39   668.4 1870.35
   678.3 1876.39   737.4 1917.01   766.9 1935.34   885.1 2002.54   904.8 2012.07
#Mann= 3 , 0 , 0
       0     .08       0   516.3    .045       0   541.3     .08       0
Bank Sta=516.3,541.3
XS Rating Curve= 0 ,0
Exp/Cntr=0.3,0.1

Type RM Length L Ch R = 1 ,3333.6  ,494.5,518.1,539.5
XS GIS Cut Line= 4
     1845234.462      155454.827     1845003.145      155716.689
     1845055.448      156094.013     1844856.635      156336.322
#Sta/Elev= 30
      10 2079.88    59.9 2067.21   109.8 2050.37   149.7 2033.17   209.6 2001.58
   229.6 1989.32   249.6 1974.15   259.6 1965.62   299.5  1927.8   319.4 1910.04
   329.4 1902.08   349.4 1890.39   379.5 1877.87   409.5 1867.41   439.6 1857.93
   479.7 1847.35   499.8 1841.08   537.4 1825.02   549.9 1823.15   562.4 1824.57
     600 1831.26   700.3 1861.15   710.3 1864.93   740.4 1881.33   801.1 1909.99
   841.5 1926.91   892.1 1946.68   912.3    1957   942.7 1975.65  1043.8 2041.69
#Mann= 3 , 0 , 0
       0     .08       0   537.4    .045       0   562.4     .08       0
Bank Sta=537.4,562.4
XS Rating Curve= 0 ,0
Exp/Cntr=0.3,0.1

Type RM Length L Ch R = 1 ,2815.5  ,195,219.5,244.2
XS GIS Cut Line= 4
     1845145.061      155398.998     1844787.201      155497.678
     1844436.868      155930.817     1844460.364       156148.43
#Sta/Elev= 30
      10 2076.17    30.1 2065.56    90.3 2037.57   170.6 2005.41   250.8 1967.91
   331.1 1939.04   371.2 1927.55     421 1925.86   470.7 1922.44   480.6 1921.57
   490.6 1918.39   500.5 1914.05   530.4 1897.96     610 1853.23   659.7 1824.42
   679.6 1810.07     687 1806.32   689.5 1805.05   699.5 1803.93     712 1804.81
   749.2 1814.35   848.7 1846.57   858.7 1847.41   888.5 1846.09   928.3 1846.39
   968.1 1848.33     978 1850.21  1087.5  1896.1  1117.3 1909.92  1147.2 1925.71
#Mann= 3 , 0 , 0
       0     .08       0     687    .045       0     712     .08       0
Bank Sta=687,712
XS Rating Curve= 0 ,0
Exp/Cntr=0.3,0.1

Type RM Length L Ch R = 1 ,2596    ,288.6,297.5,306.3
XS GIS Cut Line= 4
     1845152.581      155361.779     1844566.047      155574.725
     1844334.422      155574.725     1844143.892      155858.652
#Sta/Elev= 30
    10.1 2066.16    30.2 2057.97    50.3 2048.47   100.6 2027.68   191.2 1997.75
   261.7 1967.04   281.8  1959.1   362.3  1933.5   422.7 1918.47   493.2 1897.26
   503.2 1893.63   543.5  1876.7   674.3 1817.61   704.6 1803.33   712.2 1800.48
   714.6 1799.58   724.7 1798.44   737.2 1799.91     765 1806.24   855.6 1821.97
     916 1836.53   946.1 1841.95   976.3 1844.41  1086.9 1845.62    1107 1846.82
  1127.2 1852.04  1147.3 1858.94  1167.4 1868.28  1187.5 1878.49  1197.5 1882.55
#Mann= 3 , 0 , 0
       0     .08       0   712.2    .045       0   737.2     .08       0
Bank Sta=712.2,737.2
XS Rating Curve= 0 ,0
Exp/Cntr=0.3,0.1

Type RM Length L Ch R = 1 ,2298.5  ,394.9,397,399.1
XS GIS Cut Line= 4
     1845127.715      155305.182     1844816.351      155399.138
     1844424.083      155268.382     1844191.646      155143.048
#Sta/Elev= 30
     9.9 2027.46    39.4 2015.91    78.8 2001.82   108.4 1992.23   167.5 1974.22
   216.8 1958.12   236.5 1950.42   285.8 1929.22   325.2 1913.79     416 1864.45
   516.8 1808.39   534.6 1797.86     537 1796.51   547.1 1793.64   559.6  1794.4
   577.4 1797.95   587.4 1798.93   607.6 1799.23     648  1798.8   668.1 1800.32
   688.3 1804.14   698.4 1807.16   708.5 1810.94   728.6 1820.79   758.3 1837.74
   787.6 1852.73   797.4 1858.42   836.5 1883.63   953.9 1960.75  1002.8 1995.48
#Mann= 3 , 0 , 0
       0     .08       0   534.6    .045       0   559.6     .08       0
Bank Sta=534.6,559.6
XS Rating Curve= 0 ,0
Exp/Cntr=0.3,0.1