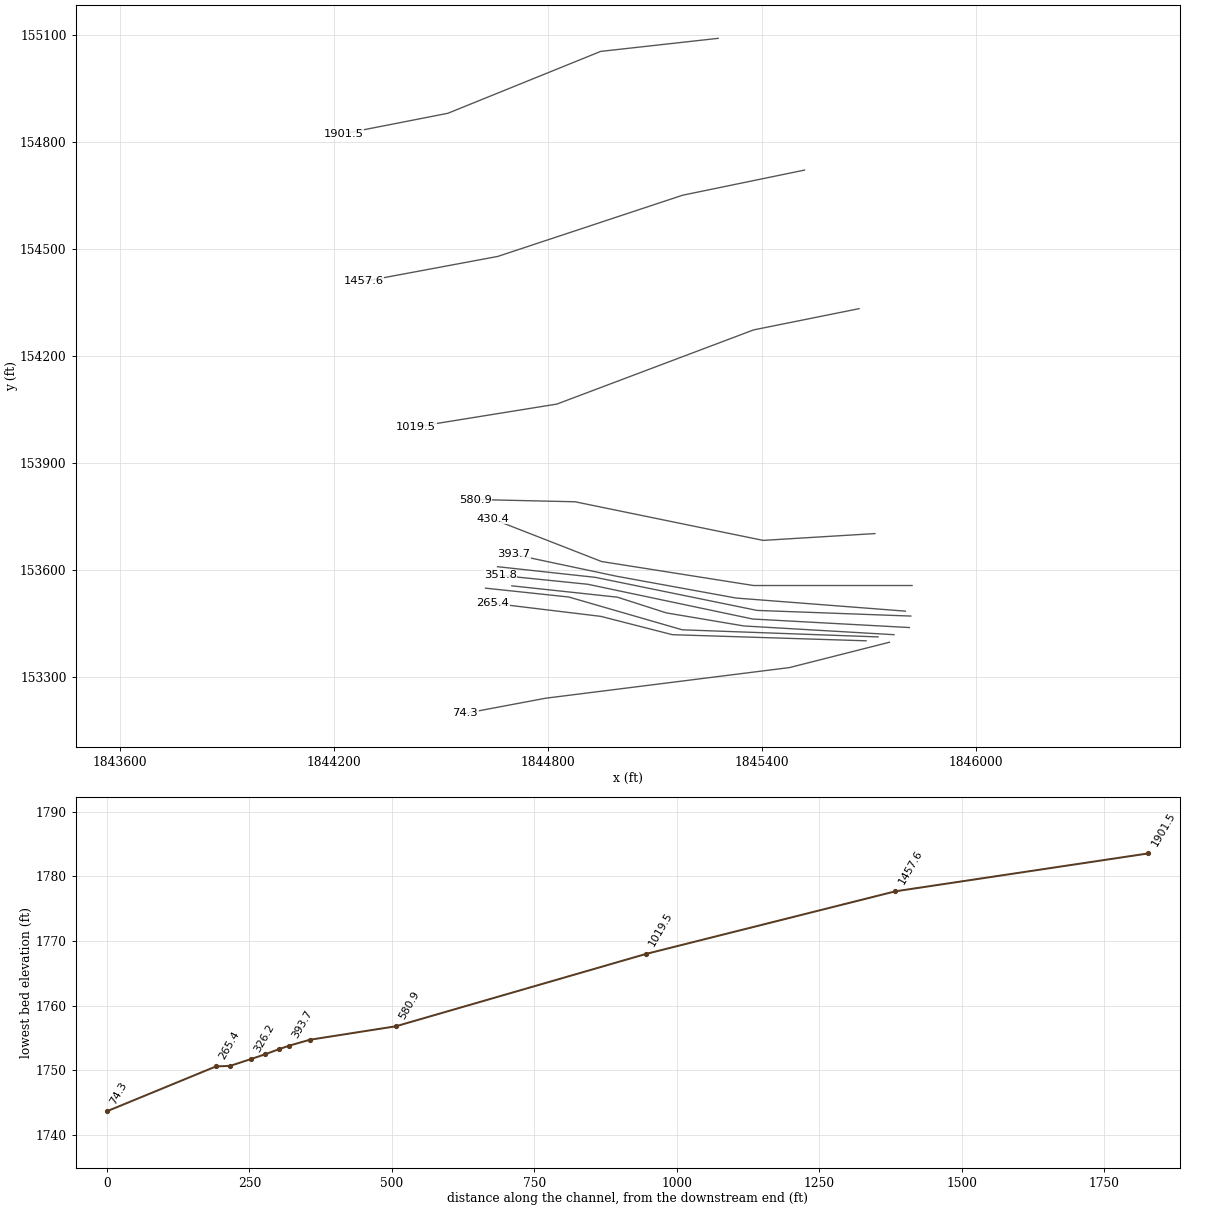
HEC-RAS study Buzzard Branch.prj: Buzzard Branch

--- Buzzard Branch.g01 (geometry) --- (continued)

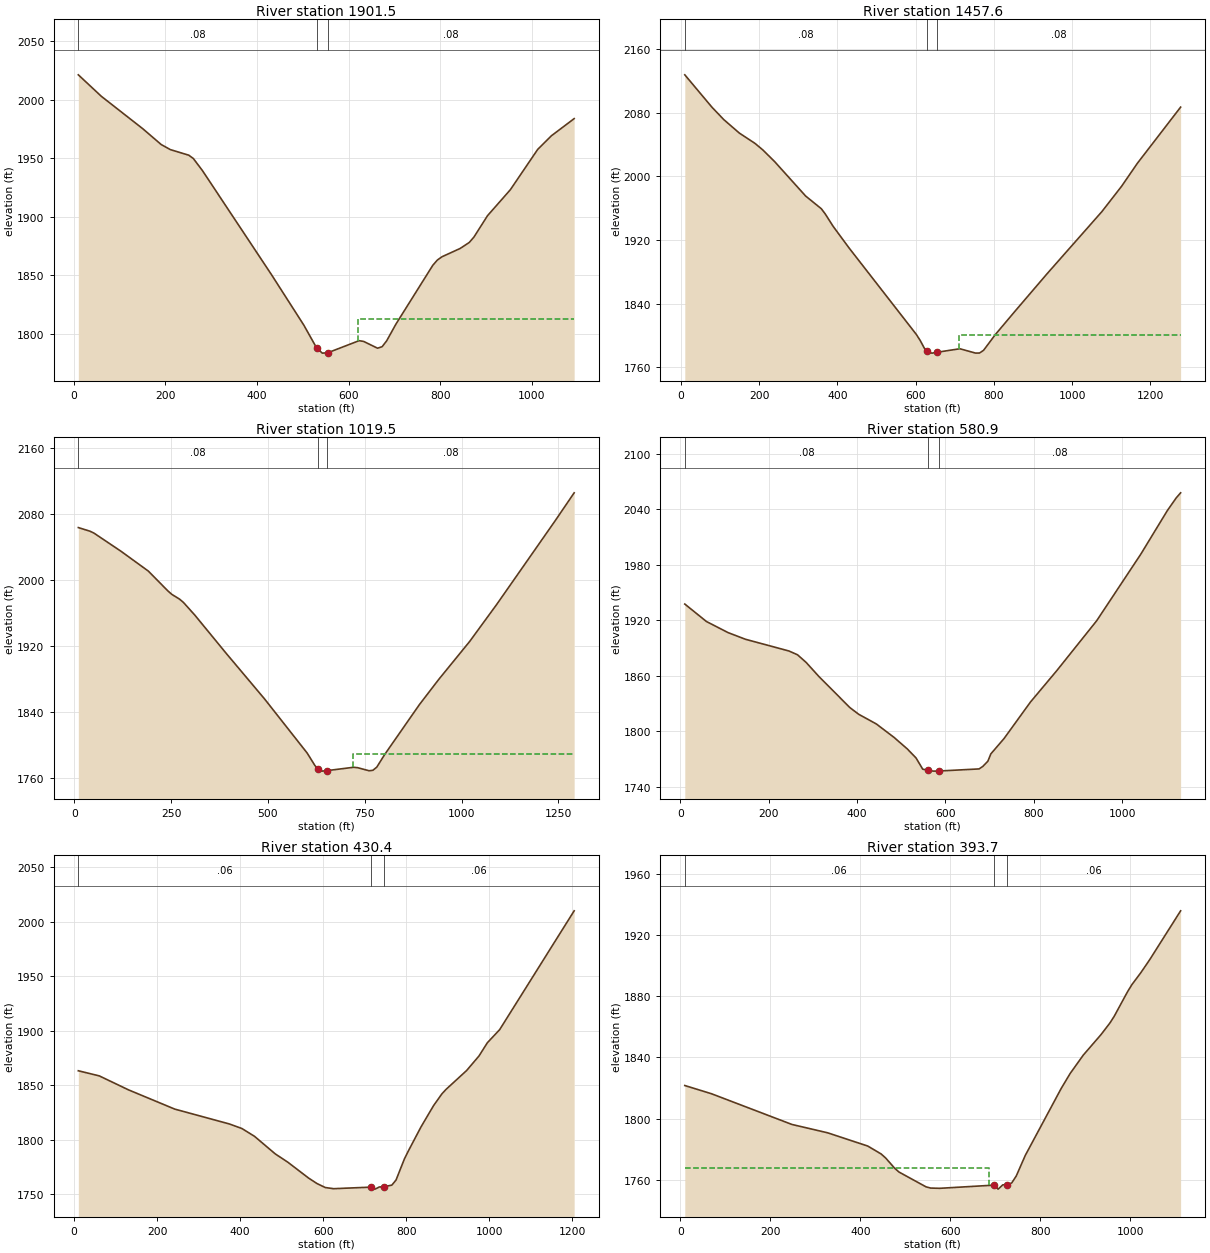
Type RM Length L Ch R = 1 ,1901.5  ,445.7,443.9,442.1
XS GIS Cut Line= 4
     1845277.667      155090.019     1844948.314      155053.407
     1844519.674      154879.819     1844226.668      154822.492
#Sta/Elev= 30
      10 2021.42    60.3 2003.04   150.6 1975.38   190.8 1961.87   210.9  1957.5
     251 1952.75   261.1 1949.89   281.2 1939.42   431.9 1850.49   502.3 1807.47
     530 1788.14   542.5 1783.57     555 1783.96   622.9  1794.2     633 1793.55
   663.1 1787.79   673.2 1789.05   683.2 1794.14   703.4 1808.43   783.8 1858.62
   793.8 1863.14   803.8 1865.92   843.6 1873.04   863.5 1878.18   873.5  1882.7
   903.3 1901.05   953.1 1923.21  1012.8 1957.67  1042.6 1969.29  1092.4 1983.98
#Mann= 3 , 0 , 0
      10     .08       0     530    .045       0     555     .08       0
#XS Ineff= 2 , 0
                          621.45         1813.12
Permanent Ineff=
       F       F
Bank Sta=530,555
XS Rating Curve= 0 ,0
Exp/Cntr=0.3,0.1

Type RM Length L Ch R = 1 ,1457.6  ,437,438.2,439.3
XS GIS Cut Line= 4
     1845519.715      154720.577      1845178.09      154650.174
     1844659.807      154478.529     1844283.995      154408.462
#Sta/Elev= 30
      10 2127.86    79.7 2086.95   109.6 2071.54   149.5 2054.53   189.4  2041.6
   209.3 2033.41   239.2 2018.89   318.9 1975.32   358.9 1959.38     369 1952.75
   389.2 1937.16   429.7 1910.07   601.6 1801.28   611.7 1793.51   621.8 1784.21
   629.5 1779.85   631.9 1778.49     642  1777.7   654.5 1778.76   712.8 1783.21
   753.2 1777.74   763.3 1777.86   773.4 1781.18   803.8 1801.17   854.3 1830.66
     935 1877.11  1075.9 1955.77  1126.2 1987.62  1166.4 2016.43  1277.1 2087.22
#Mann= 3 , 0 , 0
      10     .08       0   629.5    .045       0   654.5     .08       0
#XS Ineff= 2 , 0
                          711.15         1801.05
Permanent Ineff=
       F       F
Bank Sta=629.5,654.5
XS Rating Curve= 0 ,0
Exp/Cntr=0.3,0.1

Type RM Length L Ch R = 1 ,1019.5  ,454.2,438.5,422.7
XS GIS Cut Line= 4
     1845672.587      154332.026     1845376.964      154272.476
     1844825.419      154064.499     1844430.498      154000.802
#Sta/Elev= 30
    10.1 2063.71    40.2  2059.3    50.3 2057.04   120.6 2034.87     191 2010.85
   241.2 1986.92   251.3 1982.72   271.4  1976.9   281.5  1972.9   311.6 1957.12
   391.5 1911.33   491.4 1855.53   601.3 1789.92   621.3 1774.79   628.7 1770.81
   631.3 1769.42   641.2 1767.99   653.7 1768.67   721.2 1772.66   731.2 1772.21
   761.1 1768.46   771.1 1769.01   781.1 1772.82   801.1 1787.88     891 1848.61
     941 1879.24    1021 1925.39    1091 1970.43    1241 2071.35    1291  2105.9
#Mann= 3 , 0 , 0
    10.1     .08       0   628.7    .045       0   653.7     .08       0
#XS Ineff= 2 , 0
                          719.34         1788.71
Permanent Ineff=
       F       F
Bank Sta=628.7,653.7
XS Rating Curve= 0 ,0
Exp/Cntr=0.3,0.1

Type RM Length L Ch R = 1 ,580.9   ,149.3,150.6,151.9
XS GIS Cut Line= 4
     1845717.175      153701.427     1845403.667      153682.323
     1844876.376      153790.602      1844596.11      153796.972
#Sta/Elev= 30
     9.8 1937.33    58.9 1918.44     108 1906.43   147.2 1899.28   245.4 1886.65
     265 1882.54   284.6 1874.28   314.1 1858.75   383.9 1825.35   403.8 1818.19
   443.7 1807.73   483.6 1793.28   513.5 1780.87   533.4 1771.09   548.7 1758.88
   560.8 1757.75   573.3  1756.8   585.8 1756.92  676.28 1759.19  684.83 1761.93
  696.24 1767.58   702.9 1775.42   732.8 1792.01   792.6 1831.45   852.4 1865.47
   942.5 1919.23  1042.6  1991.3  1102.7 2038.39  1122.7 2052.02  1132.7 2057.52
#Mann= 3 , 0 , 0
     9.8     .08       0   560.8    .045       0   585.8     .08       0
Bank Sta=560.8,585.8
XS Rating Curve= 0 ,0
Exp/Cntr=0.3,0.1

Type RM Length L Ch R = 1 ,430.4   ,37.2,36.6,36.1
XS GIS Cut Line= 4
     1845821.305      153555.791     1845376.734      153555.791
     1844950.843      153623.037       1844644.5      153742.585
#Sta/Elev= 30
    10.1 1863.24    60.6 1858.53   131.4 1845.66   242.5 1828.07   373.8 1814.49
   404.2 1810.28   434.5 1803.14   484.7 1786.97   514.8 1779.41   564.9 1764.84
     585 1759.85     605 1756.19   625.1 1755.12   715.3 1756.55  725.02 1754.72
   735.4 1756.71   745.4 1756.85   765.4 1758.39   775.5 1763.08   795.5 1782.26
   805.5 1789.95   835.6 1811.72   865.7 1831.16   885.7 1841.93   895.7 1846.08
   945.5 1863.44   975.4 1876.83   995.3 1888.83  1025.2 1900.97  1204.6 2009.87
#Mann= 3 , 0 , 0
    10.1     .06       0   715.3    .045       0   745.4     .06       0
Bank Sta=715.3,745.4
XS Rating Curve= 0 ,0
Exp/Cntr=0.3,0.1

Type RM Length L Ch R = 1 ,393.7   ,17.9,17.3,16.7
XS GIS Cut Line= 4
     1845802.434      153483.967     1845327.853      153520.662
      1844992.71      153581.819     1844704.047      153642.977
#Sta/Elev= 30
     9.9 1821.59    69.4 1816.19   247.9 1796.12   327.2 1790.66   416.5 1781.98
   446.2 1776.81   456.2 1774.18     476 1767.55     486 1764.96   546.1 1755.27
   556.2  1754.5   576.2 1754.33   696.4  1756.4  706.21  1753.8   716.5  1756.6
   726.5  1756.7   736.5 1757.89   746.5 1762.42   766.6 1775.92   846.2  1819.6
   865.9 1829.32   895.4 1841.49   934.7 1854.87   954.4 1862.42   964.2 1866.93
   993.7 1882.93  1003.6 1887.67  1023.2 1895.38  1042.9 1903.88  1111.7 1935.89
#Mann= 3 , 0 , 0
     9.9     .06       0   696.4    .045       0   726.5     .06       0
#XS Ineff= 2 , 0
          685.23  1767.3
Permanent Ineff=
       F       F
Bank Sta=696.4,726.5
XS Rating Curve= 0 ,0
Exp/Cntr=0.3,0.1

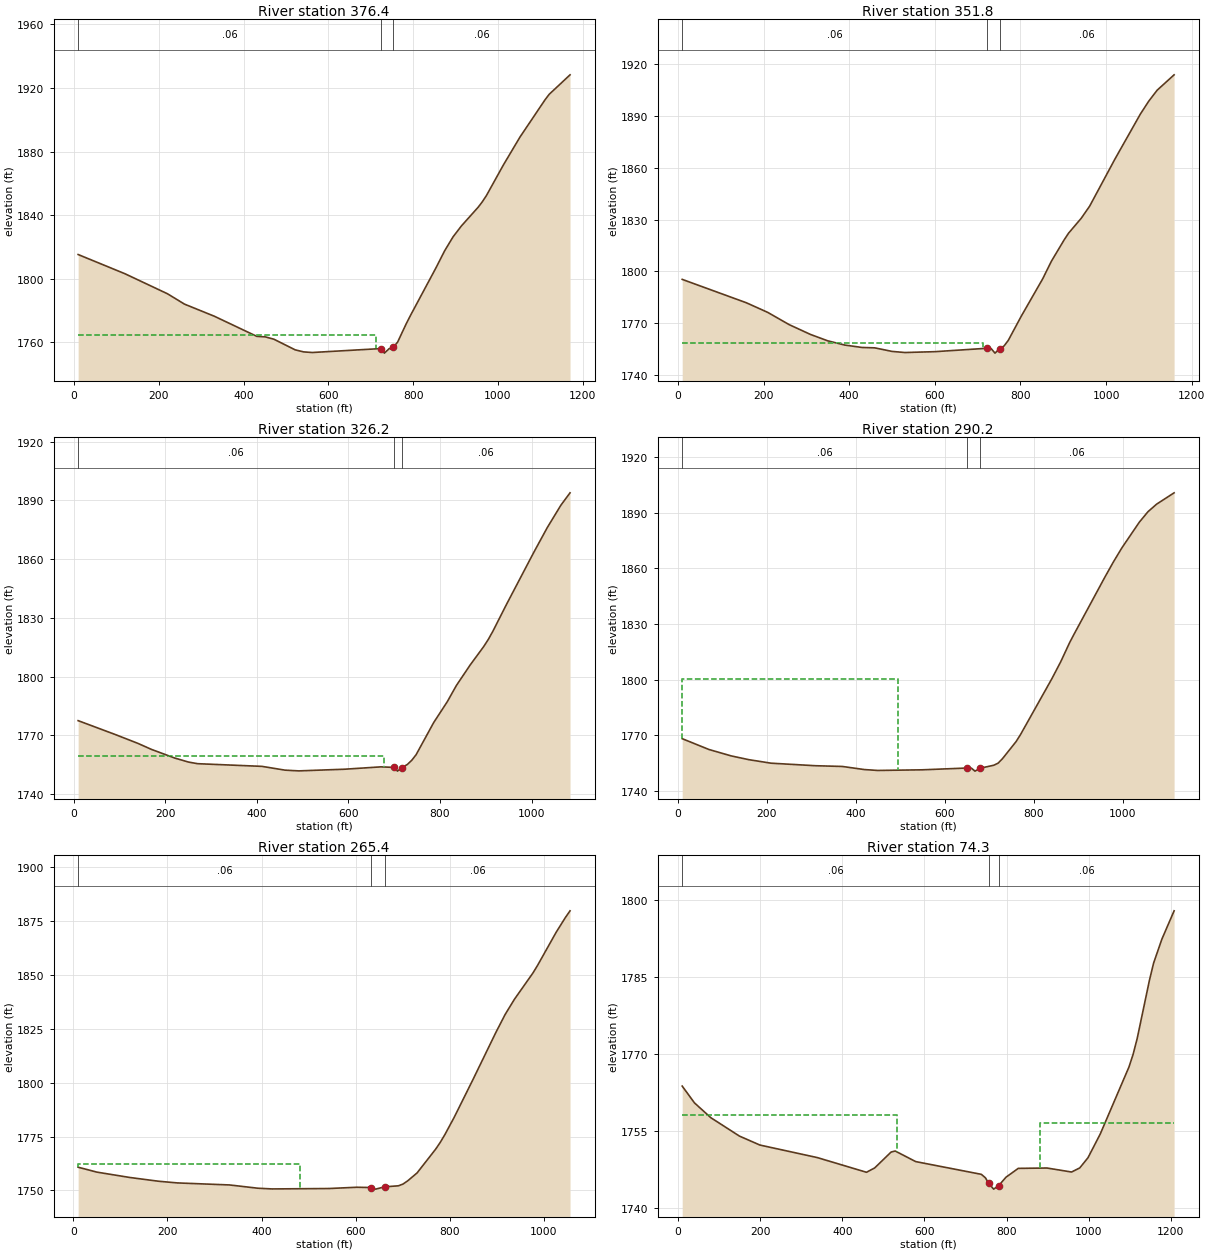
Type RM Length L Ch R = 1 ,376.4   ,24.8,24.7,24.5
XS GIS Cut Line= 4
     1845817.772      153470.153     1845386.739       153485.97
     1844933.234      153578.692     1844659.124      153608.558
#Sta/Elev= 30
      10 1815.28   120.4 1803.19   220.7 1790.59   260.8 1784.08     331 1776.49
   431.3 1763.82   451.4 1763.48   471.6 1762.02   521.9 1755.32     542 1754.03
   562.1 1753.66   723.1 1756.12  732.18 1753.27   743.3 1756.06   753.3 1756.94
   763.4 1760.24   783.5 1771.66   793.6 1776.94     854 1807.03   874.1 1817.56
   894.2 1826.44   913.9  1833.3   953.3 1845.03   963.1 1848.45     973 1852.48
  1012.4 1871.44  1051.8 1889.12  1110.9 1912.56  1120.7 1916.01  1169.9 1928.27
#Mann= 3 , 0 , 0
      10     .06       0   723.1    .045       0   753.3     .06       0
#XS Ineff= 2 , 0
          712.64 1764.45
Permanent Ineff=
       F       F
Bank Sta=723.1,753.3
XS Rating Curve= 0 ,0
Exp/Cntr=0.3,0.1

Type RM Length L Ch R = 1 ,351.8   ,28.5,25.6,22.7
XS GIS Cut Line= 4
     1845813.818      153437.947      1845374.68      153461.815
     1844912.213      153559.277     1844667.033      153584.261
#Sta/Elev= 30
      10 1795.27   159.9 1781.69   209.9  1776.1   259.9    1769   309.8  1763.3
   349.8 1759.62   389.8 1757.15   429.8 1755.76   459.9 1755.53   500.1 1753.46
   530.3 1752.82   600.7 1753.32   721.3 1755.28   731.4 1755.16  740.56 1752.47
   751.5  1755.1   761.6 1756.59   771.6 1759.86   801.8 1773.85   852.1 1795.64
   872.2 1805.75   902.4 1818.32   912.4 1822.07     942 1830.73   961.7 1837.78
  1020.8 1865.13    1080 1891.15  1099.7  1898.7  1119.4 1905.07  1158.9 1913.97
#Mann= 3 , 0 , 0
      10     .06       0   721.3    .045       0   751.5     .06       0
#XS Ineff= 2 , 0
          712.05 1758.59
Permanent Ineff=
       F       F
Bank Sta=721.3,751.5
XS Rating Curve= 0 ,0
Exp/Cntr=0.3,0.1

Type RM Length L Ch R = 1 ,326.2   ,35.1,35.9,36.8
XS GIS Cut Line= 5
     1845770.632      153417.917     1845349.869       153442.38
     1845132.149      153479.075     1844995.157      153523.108
     1844699.155       153554.91
#Sta/Elev= 30
      10  1777.5    90.3 1770.48   140.5 1765.89   170.6 1762.76   220.8  1758.4
   250.9 1756.34   270.9 1755.51   411.4 1754.14   461.6 1752.21   491.7 1751.83
   592.1 1752.69     671 1753.89   699.8 1753.62  707.15 1751.71  716.15 1753.41
   728.6 1755.09   738.2 1757.21   747.8 1760.08   786.2 1776.51   815.9 1787.18
   835.8 1795.47   865.5 1805.82   895.3 1815.31   905.2  1818.9   915.2 1823.07
   944.9 1836.77  1004.5 1863.37  1034.2 1876.13    1064  1887.6  1083.9 1893.89
#Mann= 3 , 0 , 0
      10     .06       0   699.8    .045       0  716.15     .06       0
#XS Ineff= 2 , 0
          676.91 1759.51
Permanent Ineff=
       F       F
Bank Sta=699.8,716.15
XS Rating Curve= 0 ,0
Exp/Cntr=0.3,0.1

Type RM Length L Ch R = 1 ,290.2   ,24,24.8,25.6
XS GIS Cut Line= 4
     1845726.104      153411.712     1845176.957      153431.591
     1844858.899       153523.53     1844625.325      153548.378
#Sta/Elev= 30
      10 1768.17    69.9 1762.35   119.9 1758.89   159.9 1756.84   209.8 1754.95
   309.7 1753.58   369.7 1753.19   419.6 1751.51   449.6 1751.03   549.5 1751.38
   649.8 1752.34   659.9 1752.27  668.05 1750.67   679.9 1752.26     710 1753.82
   720.1 1754.98   730.1 1757.47   760.2 1766.54   770.2 1770.32   840.5 1800.36
   860.5 1809.53   880.6 1819.89   890.4 1824.37   958.9 1854.79   978.5  1863.2
     998 1870.97  1037.2 1884.82  1056.8 1890.52  1076.3  1894.6  1115.5 1900.69
#Mann= 3 , 0 , 0
      10     .06       0   649.8    .045       0   679.9     .06       0
#XS Ineff= 2 , 0
          495.29 1800.44
Permanent Ineff=
       F       F
Bank Sta=649.8,679.9
XS Rating Curve= 0 ,0
Exp/Cntr=0.3,0.1

Type RM Length L Ch R = 1 ,265.4   ,180.1,191.2,202.2
XS GIS Cut Line= 4
     1845692.351      153400.793     1845149.273      153417.917
     1844948.677       153469.29     1844645.336      153505.984
#Sta/Elev= 30
    10.1 1760.77    50.3 1758.47   120.7 1755.98   181.1 1754.25   221.4 1753.47
     332 1752.53   392.4 1751.01   422.6 1750.68   543.3 1750.87   602.5 1751.46
   632.1 1751.33  642.72 1750.59   661.7 1751.65   691.3 1752.14   701.1 1752.98
     711 1754.47   730.7  1758.1   770.1 1769.11     780 1772.29   789.8 1775.89
   809.6 1783.92     849 1801.22   898.3 1823.38     918 1831.72   937.7 1838.77
   977.1 1850.99     987 1854.54  1026.4 1869.88  1046.1 1876.76    1056 1879.87
#Mann= 3 , 0 , 0
    10.1     .06       0   632.1    .045       0   661.7     .06       0
#XS Ineff= 2 , 0
          481.53 1762.21
Permanent Ineff=
       F       F
Bank Sta=632.1,661.7
XS Rating Curve= 0 ,0
Exp/Cntr=0.3,0.1

Type RM Length L Ch R = 1 ,74.3    ,68.9,74.3,79.6
XS GIS Cut Line= 4
     1845757.795      153396.703     1845477.603      153325.721
     1844793.936      153239.796     1844568.172      153197.297
#Sta/Elev= 30
      10 1763.71    39.9 1760.44    79.7 1757.56   149.5 1753.97   199.3 1752.23
     339 1749.79   458.8 1746.93   478.8 1747.78   518.7 1750.87   528.7 1751.07
   578.6 1749.01   738.4 1746.53   748.4 1745.85   755.9 1744.81   768.4 1743.65
   780.9 1744.35   798.3 1745.96   828.3 1747.69   898.2 1747.76   958.1 1746.98
   978.1 1747.78   998.1 1749.76    1028 1754.39  1097.9 1767.43  1107.9 1769.87
  1117.9 1772.97  1147.9 1784.37  1157.9 1787.66  1177.9 1792.29  1207.8 1797.83
#Mann= 3 , 0 , 0
      10     .06       0   755.9    .045       0   780.9     .06       0
#XS Ineff= 2 , 0
          532.48 1758.14  880.81         1756.52
Permanent Ineff=
       F       F
Bank Sta=755.9,780.9
XS Rating Curve= 0 ,0
Exp/Cntr=0.3,0.1

Chan Stop Cuts=-1
Use User Specified Reach Order=0